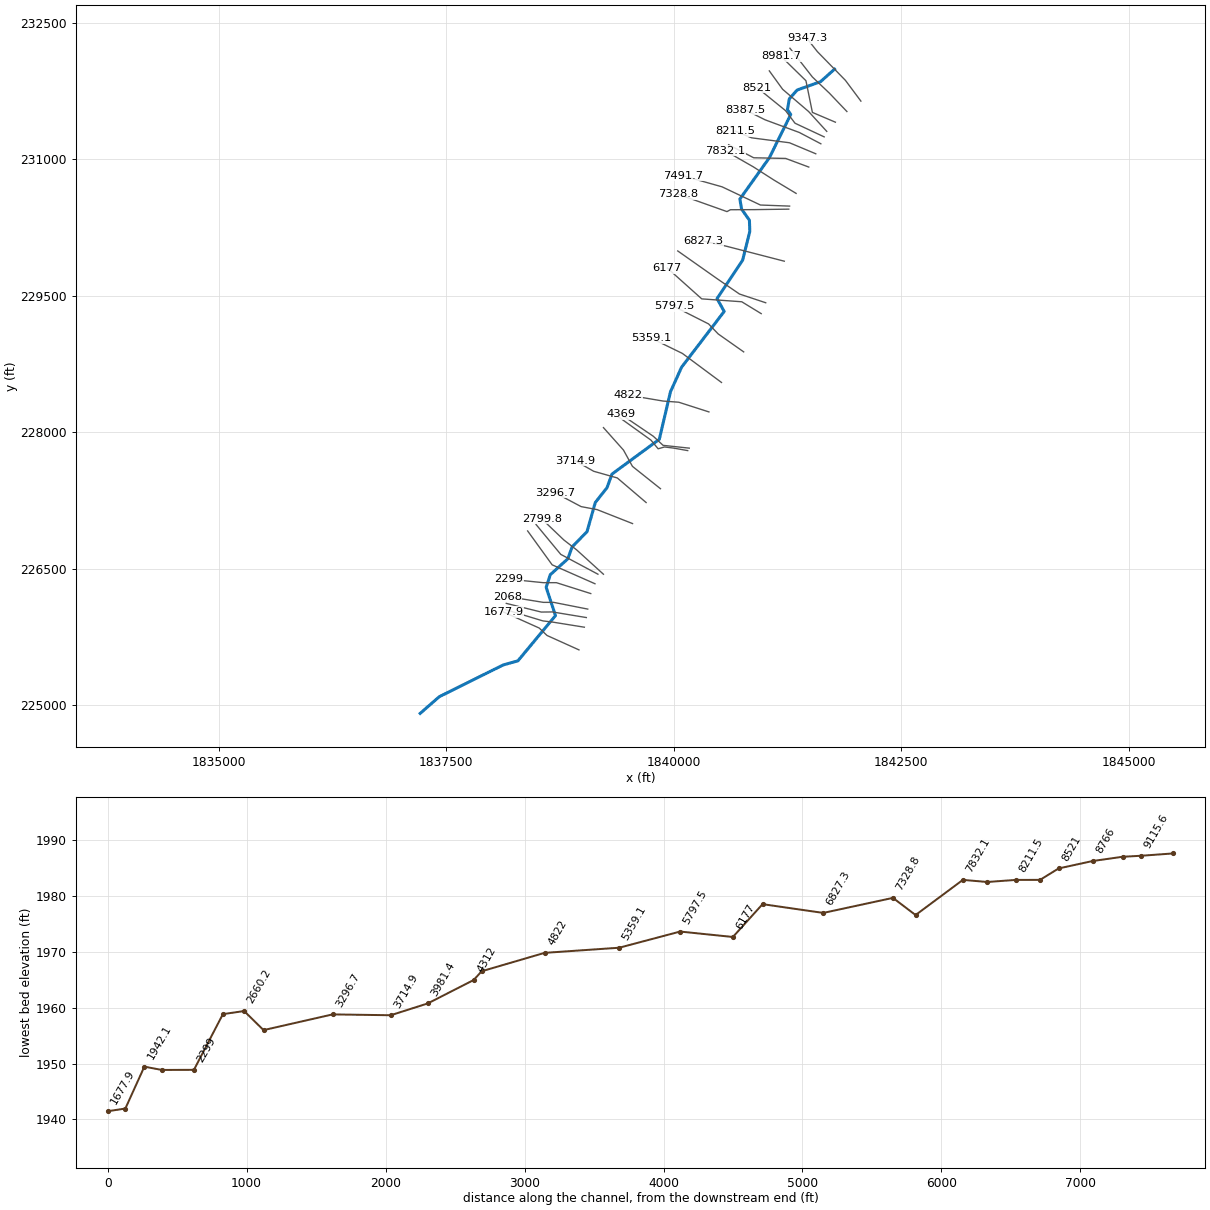
--- BlackFk.prj (project) ---

Proj Title=BlackFk
Current Plan=p01
Default Exp/Contr=0,0
English Units
Geom File=g01
Flow File=f01
Plan File=p01
BEGIN DESCRIPTION:
END DESCRIPTION:
DSS Export Rating Curves= 0
DSS Export Rating Curve Sorted= 0
DSS Export Volume Flow Curves= 0
DXF OffsetX= 0
DXF OffsetY= 0
DXF ScaleX= 0
DXF ScaleY= 0

--- BlackFk.p01 (plan) ---

Plan Title=Floodplain
Program Version=4.00
Geom File=g01
Flow File=f01
K Sum by GR=0
Std Step Tol=0.01
Critical Tol=0.01
Num of Std Step Trials=20
Max Error Tol=0.3
Flow Tol Ratio=0.001
Split Flow NTrial=30
Split Flow Tol=0.02
Split Flow Ratio=0.02
Log Output Level=0
Friction Slope Method=1
Unsteady Friction Slope Method=2
Unsteady Bridges Friction Slope Method=1
Global Log Level=0
CheckData=False
Run HTab=0
Run UNet=0
Run PostProcess=0
UNET Theta=0
UNET Theta Warmup=0
UNET ZTol=0
UNET ZSATol=0
UNET MxIter=0
UNET MaxInSteps=0
UNET DtIC=0
UNET DtMin=0
UNET MaxCRTS=0
UNET WFStab=0
UNET SFStab=0
UNET WFX=0
UNET SFX=0
UNET DSS MLevel=0
UNET DZMax Abort=0
UNET Convert EG Bridges=0
UNET Use Existing IB Tables=0
UNET Froude Limit=0
UNET Froude Power=0
Write IC File=0
Echo Input=False
Echo Output=False
Write Detailed=0

--- BlackFk.f01 (steady flow) ---

Flow Title=NFF Regression Equation
Program Version=4.00
Number of Profiles=1
Profile Names=P100yr
River Rch & RM=BlackFk,Main      ,9347.3
521.4917
River Rch & RM=BlackFk,Main      ,9115.6
612.8662
River Rch & RM=BlackFk,Main      ,8211.5
668.7890
River Rch & RM=BlackFk,Main      ,5797.5
733.9434
River Rch & RM=BlackFk,Main      ,5797.5
836.8581
River Rch & RM=BlackFk,Main      ,3981.4
888.3540
River Rch & RM=BlackFk,Main      ,1677.9
962.9301
River Rch & RM=BlackFk,Main      ,1496.2
1058.466
River Rch & RM=BlackFk,Main      ,212.8
1079.526
Boundary for River Rch & Prof#=BlackFk,Main      ,1
Up Type=0
Dn Type=3
Dn Slope=0.130743

--- BlackFk.g01 (geometry) ---

Geom Title=USGS 10m DEM
Program Version=4.00

River Reach=BlackFk         ,Main
Reach XY= 30
     1841766.111       231988.26     1841611.533      231850.171
     1841355.279      231758.799     1841269.403      231663.305
     1841248.048      231542.973     1841284.517      231490.178
     1841048.873      231013.393     1840725.735      230560.677
      1840743.84      230450.732     1840830.404      230328.445
     1840834.526      230204.783     1840755.919      229889.444
      1840474.35      229466.625     1840553.133       229325.84
     1840084.871      228712.925     1839962.491      228441.508
     1839840.353      227920.792     1839320.103      227538.529
     1839266.027      227389.353     1839136.897      227226.659
     1839045.527      226905.465     1838882.226      226738.548
     1838835.144      226607.701     1838642.207      226432.852
     1838596.987      226294.179     1838699.485      225983.671
     1838286.596      225486.431     1838125.525      225441.708
      1837422.89      225092.791     1837212.797      224909.309

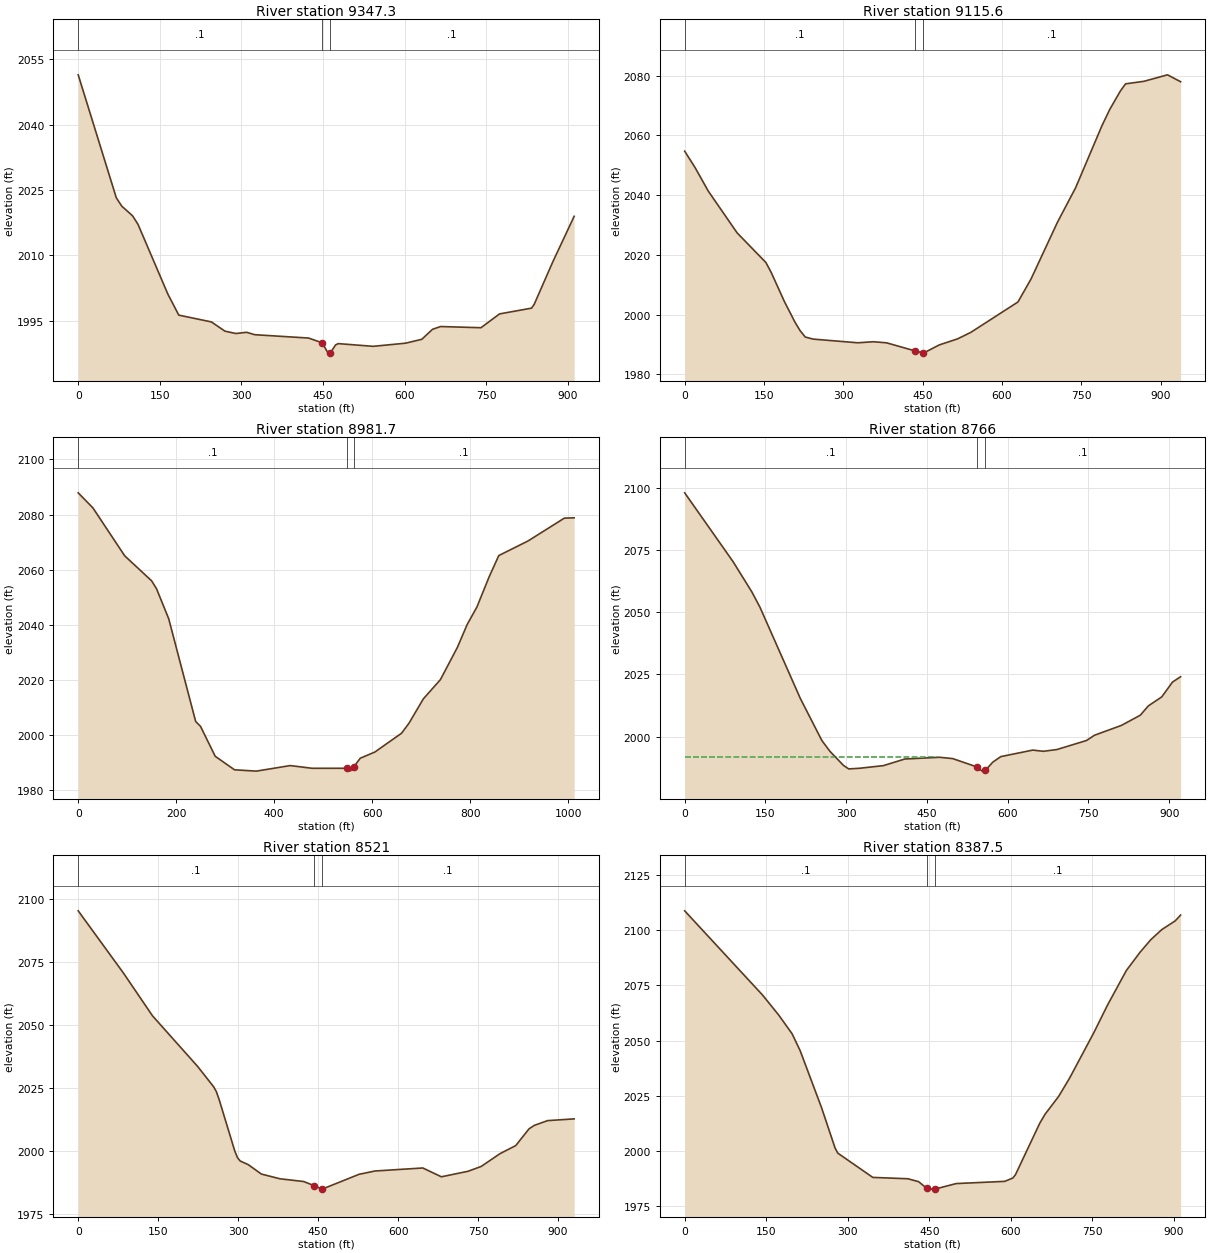
Type RM Length L Ch R = 1 ,9347.3  ,230.7,231.7,232.7
XS GIS Cut Line= 4
     1842055.299      231636.841     1841885.079      231865.195
      1841577.13      232180.693     1841461.763      232326.634
#Sta/Elev= 30
       0 2051.41      70 2023.21      80 2021.29    99.9 2019.07   109.9 2017.11
   164.9 2001.08   184.9 1996.28   244.8 1994.72   269.8  1992.6   289.8 1992.06
   309.6 1992.34   324.4 1991.79   423.5 1991.02   448.5 1989.93   458.2 1987.82
   463.2 1987.56   463.5 1987.62   473.1 1989.44     478 1989.74   542.4 1989.12
   601.8 1989.84   631.6 1990.73   651.4 1993.03   666.2 1993.66   740.4 1993.39
   774.6 1996.56   833.4 1997.88   838.3 1998.77   872.6 2008.54   911.7 2018.95
#Mann= 3 , 0 , 0
       0      .1       0   448.5    .045       0   463.5      .1       0
Bank Sta=448.5,463.5
XS Rating Curve= 0 ,0
Exp/Cntr=0.3,0.1

Type RM Length L Ch R = 1 ,9115.6  ,147.9,134,120
XS GIS Cut Line= 4
     1841901.553      231522.434     1841709.971      231723.297
     1841522.785      231901.424     1841275.424       232218.02
#Sta/Elev= 30
       0 2054.71    19.8 2049.18    44.6 2041.36    99.1 2027.39   153.7 2017.43
   163.6 2014.13   188.4 2004.46   208.2 1997.62   218.1 1994.69     228 1992.52
   242.9 1991.83   327.3  1990.6   357.1 1990.95   381.9 1990.58   436.4 1987.84
   451.4 1987.14   481.3 1989.88   516.1 1991.92   540.9 1994.07   630.2 2004.26
     655 2011.99   704.6 2030.84   739.3 2042.52   788.9 2063.21   803.8 2068.69
   823.7 2074.81   833.6 2077.23   868.3 2078.08   912.9 2080.25   937.7 2077.94
#Mann= 3 , 0 , 0
       0      .1       0   436.4    .045       0   451.4      .1       0
Bank Sta=436.4,451.4
XS Rating Curve= 0 ,0
Exp/Cntr=0.3,0.1

Type RM Length L Ch R = 1 ,8981.7  ,200.7,215.6,230.5
XS GIS Cut Line= 4
     1841775.127      231405.208     1841522.407      231512.666
     1841451.528      231860.918     1841178.399       232128.11
#Sta/Elev= 30
       0 2087.89      30 2082.43    94.9 2065.04   149.8 2055.98   159.8 2053.12
   184.7 2042.22   239.7 2004.97   249.6  2003.2   279.6 1992.34     319 1987.44
   363.5 1986.96   432.6 1988.97     477    1988   547.7 1987.99     556 1987.08
   562.7  1988.6   575.7 1991.65   605.3 1993.87   659.8  2000.7   674.7 2004.24
   704.4 2013.18   739.2 2020.15   773.9 2031.87   793.8 2040.14   813.6 2046.46
   838.4 2057.33   858.3 2065.14   917.8 2070.41   992.2 2078.72  1012.1 2078.82
#Mann= 3 , 0 , 0
       0      .1       0   547.7    .045       0   562.7      .1       0
Bank Sta=547.7,562.7
XS Rating Curve= 0 ,0
Exp/Cntr=0.3,0.1

Type RM Length L Ch R = 1 ,8766    ,250.8,245,184.8
XS GIS Cut Line= 4
     1841680.125      231304.269     1841481.293      231521.918
     1841195.316      231766.715     1841048.896      231969.187
#Sta/Elev= 30
       0 2097.89    89.9 2070.26   124.9 2058.08   139.9 2051.95   214.8 2015.37
   254.8 1998.48   269.8 1994.15   294.8 1988.52   304.7 1987.09   324.5 1987.34
   369.1 1988.41   408.7 1991.05   473.1 1991.76   497.9 1991.23   543.7 1987.81
   552.4  1986.2   558.7 1986.57   572.2 1989.79     587 1992.02   646.5 1994.64
   666.3 1994.16   691.2 1994.86   746.2 1998.48   761.2 2000.61   811.2 2004.55
   846.2 2008.64   861.1 2012.37   886.1    2016   906.1 2021.96   921.1 2024.09
#Mann= 3 , 0 , 0
       0      .1       0   543.7    .045       0   558.7      .1       0
#XS Ineff= 2 , 0
          469.68 1991.77
Permanent Ineff=
       F       F
Bank Sta=543.7,558.7
XS Rating Curve= 0 ,0
Exp/Cntr=0.3,0.1

Type RM Length L Ch R = 1 ,8521    ,120.1,133.5,201.4
XS GIS Cut Line= 4
     1841651.736      231243.948     1841331.441        231393.8
     1841227.345      231532.214     1840913.914      231786.161
#Sta/Elev= 30
       0 2095.41    84.7 2070.74   139.4 2053.69   224.1 2033.58     254 2025.53
     259 2023.65     264 2020.68   293.8 1999.92   298.8 1997.36   303.8 1996.04
   318.8 1994.61   343.6 1990.85   378.4 1988.98   422.9 1987.89   442.7 1986.24
   442.7 1986.23   457.5 1984.87   457.7 1984.88   526.8 1990.76   556.7 1992.07
   646.3 1993.27   681.2 1989.77     731 1991.95   755.9 1993.88   790.8 1998.92
   820.6 2002.16   845.5  2008.8   855.5 2010.19   880.4 2012.08   930.2 2012.77
#Mann= 3 , 0 , 0
       0      .1       0   442.7    .045       0   457.7      .1       0
Bank Sta=442.7,457.7
XS Rating Curve= 0 ,0
Exp/Cntr=0.3,0.1

Type RM Length L Ch R = 1 ,8387.5  ,170.8,175.9,181.1
XS GIS Cut Line= 4
     1841615.348      231167.979     1841379.221      231292.003
     1841002.961      231431.165      1840784.58      231540.403
#Sta/Elev= 30
       0 2108.68   143.2  2070.6   172.9 2061.57   197.6 2053.07   212.4 2045.43
   251.9 2019.55   276.6 2001.42   281.6 1999.11     346 1988.13   410.4 1987.52
   430.2 1986.21   445.6 1983.12     450 1982.83   460.6 1982.87   499.5 1985.35
   588.6 1986.34   603.5 1987.85   608.4 1989.37     653  2012.6   662.9 2016.73
   687.8 2024.77   707.8 2032.98   752.6 2053.63   777.5 2065.98   812.4 2081.73
   837.3 2089.89   857.2 2095.61   877.2 2100.14   902.1 2104.13   912.1 2106.76
#Mann= 3 , 0 , 0
       0      .1       0   445.6    .045       0   460.6      .1       0
Bank Sta=445.6,460.6
XS Rating Curve= 0 ,0
Exp/Cntr=0.3,0.1

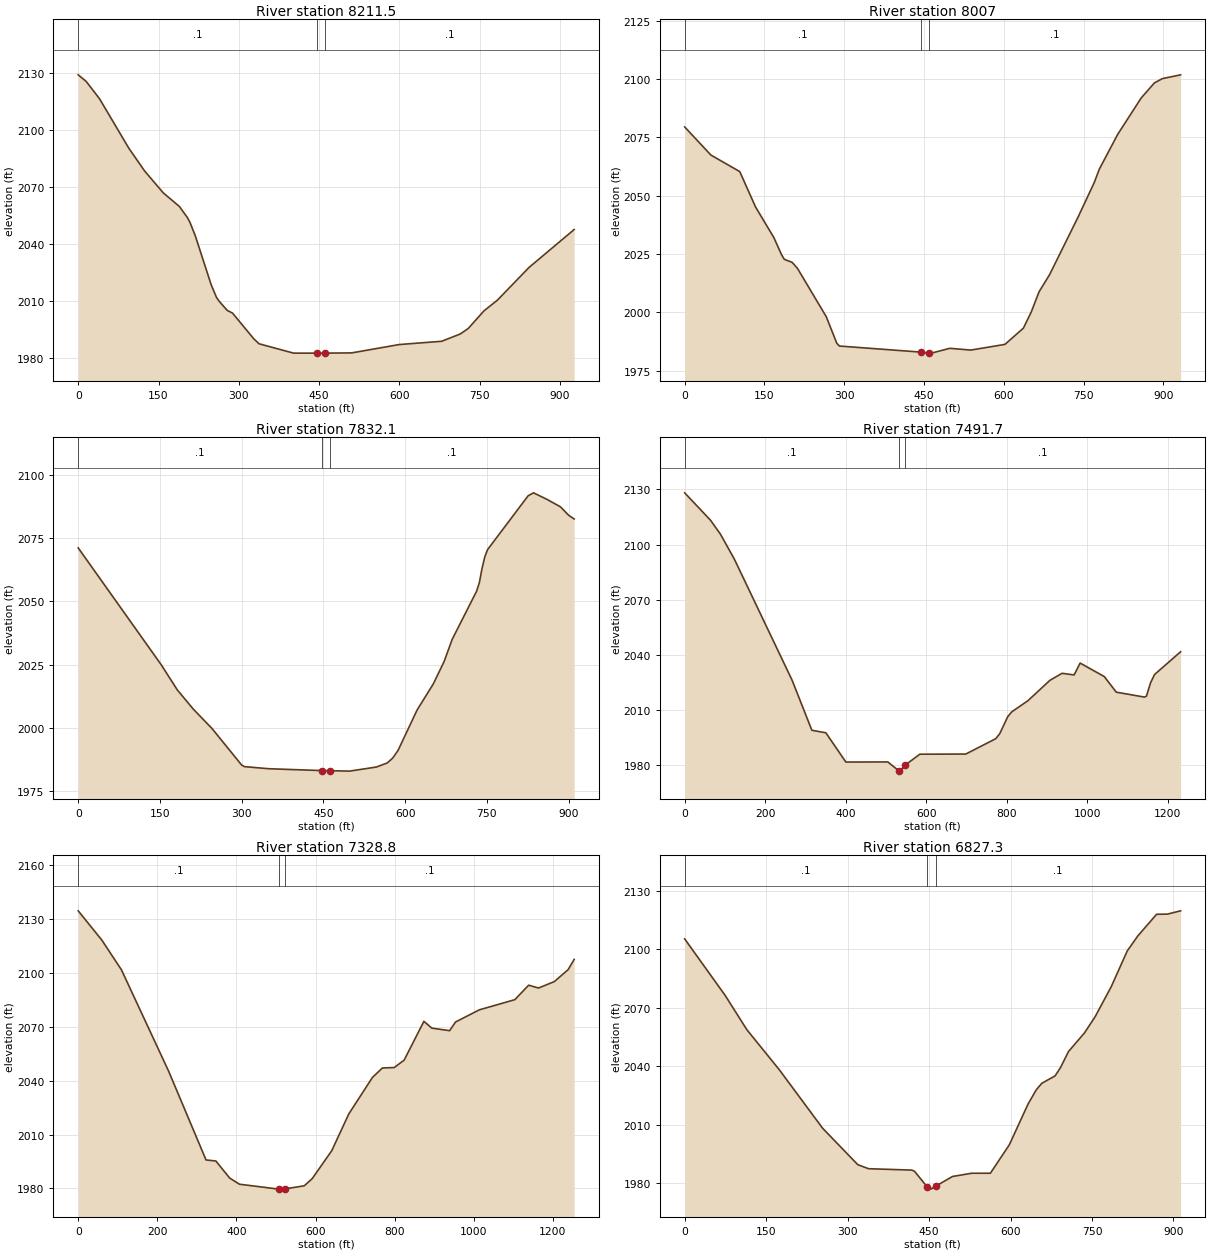
Type RM Length L Ch R = 1 ,8211.5  ,201.5,204.5,208.1
XS GIS Cut Line= 4
     1841559.384      231058.252     1841270.553      231179.175
     1840853.915      231233.519     1840675.332      231307.003
#Sta/Elev= 30
       0 2128.96    14.9  2125.5    39.8 2116.41    94.4 2090.49   124.2 2078.41
     159 2066.94   188.9 2059.86   203.8 2054.08   208.8 2051.47   218.7 2044.44
   248.5 2018.62   258.4 2012.04   263.4 2010.03   278.3 2005.27   288.3 2003.83
     328 1990.33   337.8 1987.73   402.1 1982.83   421.9 1982.82   446.8 1982.82
   461.8 1982.82   510.8 1982.94   599.8 1987.33   678.9 1989.04   713.5 1992.85
   728.4 1995.71     758 2005.04   782.8 2010.57   842.2 2027.83   926.4 2047.72
#Mann= 3 , 0 , 0
       0      .1       0   446.8    .045       0   461.8      .1       0
Bank Sta=446.8,461.8
XS Rating Curve= 0 ,0
Exp/Cntr=0.3,0.1

Type RM Length L Ch R = 1 ,8007    ,188,174.9,161.2
XS GIS Cut Line= 4
     1841482.568      230912.188     1841228.448      231007.035
      1840877.69      231014.194     1840602.095       231157.36
#Sta/Elev= 30
       0 2079.44    49.3 2067.39   103.6 2060.29   133.2 2045.16   167.7 2031.99
   182.5  2024.5   187.4 2022.66   202.2 2021.36   212.1  2018.8   266.3 1998.05
   286.1 1986.66     291 1985.49     445 1982.87     460  1982.5     464 1982.45
   498.5 1984.51   538.1 1983.76   602.3  1986.2   636.9 1993.14   651.6 2000.03
   666.4 2008.75   686.2 2016.09   740.4 2041.09     770  2055.5   779.8 2061.37
   814.3 2076.26   858.7 2091.94   883.3 2098.31   898.1 2100.15   932.6 2101.79
#Mann= 3 , 0 , 0
       0      .1       0     445    .045       0     460      .1       0
Bank Sta=445,460
XS Rating Curve= 0 ,0
Exp/Cntr=0.3,0.1

Type RM Length L Ch R = 1 ,7832.1  ,337.3,340.5,343.7
XS GIS Cut Line= 4
       1841343.3      230622.924     1841099.031      230769.868
     1840874.111      230913.977      1840563.52      231092.012
#Sta/Elev= 30
       0 2071.13   152.4 2024.88   181.8 2014.98   211.3 2007.34   245.7 1999.66
   299.9 1985.25   304.8 1984.62   349.4 1983.78   447.6 1983.04   462.6 1982.99
   497.8 1982.83   547.2 1984.45   567.1 1986.05     577 1987.95     587 1991.02
   621.8 2006.94   651.6 2017.29   671.5 2026.16   686.4 2034.96   731.2 2054.02
   736.2 2057.35   741.1 2062.96   746.1  2067.5   751.1 2070.38   825.7 2091.73
   835.6 2092.91   860.5 2090.31   885.3 2087.34   900.2 2084.01   910.2 2082.57
#Mann= 3 , 0 , 0
       0      .1       0   447.6    .045       0   462.6      .1       0
Bank Sta=447.6,462.6
XS Rating Curve= 0 ,0
Exp/Cntr=0.3,0.1

Type RM Length L Ch R = 1 ,7491.7  ,151.4,162.8,173.6
XS GIS Cut Line= 4
     1841272.061      230483.187     1840951.431      230495.063
     1840529.862      230694.962     1840102.355      230815.693
#Sta/Elev= 30
       0 2128.16    64.2 2113.22    88.8 2105.64   123.4 2092.03   266.6 2026.16
   315.9 1998.79   350.6 1997.43   400.3 1981.48   504.5 1981.55   531.7 1976.73
   534.3 1976.54   546.7 1979.66   583.9 1985.76   698.1 1985.84   772.5 1994.22
   782.4 1996.93   802.4 2006.26   812.4 2008.86   852.3 2014.88   907.2 2026.04
   937.2 2029.84   967.1 2028.95   982.1 2035.41    1042 2028.06  1071.9 2019.56
  1141.8 2016.88  1146.8  2017.4  1156.8 2024.57  1166.8 2029.16  1231.6 2041.58
#Mann= 3 , 0 , 0
       0      .1       0   531.7    .045       0   546.7      .1       0
Bank Sta=531.7,546.7
XS Rating Curve= 0 ,0
Exp/Cntr=0.3,0.1

Type RM Length L Ch R = 1 ,7328.8  ,507.6,501.5,495.4
XS GIS Cut Line= 5
     1841262.767      230449.751     1840884.858       230444.44
     1840621.781      230443.318     1840583.832      230422.828
     1840046.938      230613.814
#Sta/Elev= 30
       0 2134.52    59.7 2118.24   109.4 2101.65   228.8 2045.18   323.2 1995.85
   348.1 1995.27   382.9  1985.8   407.7 1982.34     507 1979.61   508.2 1979.62
   523.2 1979.76   571.5 1981.46   591.4 1985.38     641 2000.97   684.2 2021.46
   744.1 2041.82   769.1 2047.05   799.1 2047.29   824.1  2051.4   874.1 2073.01
   894.1 2069.23   939.1 2067.81   954.1 2072.64  1014.1  2079.4    1104 2085.07
    1139 2093.12    1164 2091.56    1204 2095.14    1239 2101.84    1254 2107.48
#Mann= 3 , 0 , 0
       0      .1       0   508.2    .045       0   523.2      .1       0
Bank Sta=508.2,523.2
XS Rating Curve= 0 ,0
Exp/Cntr=0.3,0.1

Type RM Length L Ch R = 1 ,6827.3  ,444.5,436.8,429.1
XS GIS Cut Line= 4
     1841213.637      229877.814     1840837.558      229975.084
     1840577.041      230042.453     1840327.575      230098.575
#Sta/Elev= 30
       0  2105.4    74.7 2076.33   114.5 2058.79   174.3  2038.2     254 2008.19
   318.7 1989.49   338.6  1987.4   418.4 1986.69   423.3 1986.05     447 1977.93
   453.2 1976.92     462 1978.41   493.1  1983.4     528 1985.07   562.9 1985.08
   597.7 1999.63   632.6 2020.79   647.6 2027.97   657.5 2031.24   682.1 2035.08
     692  2039.3   706.7 2047.54   736.2 2057.15   755.9  2065.5   785.4 2080.84
   814.9  2099.2   834.6 2107.01     869 2118.05   888.7 2118.12   913.2 2119.82
#Mann= 3 , 0 , 0
       0      .1       0     447    .045       0     462      .1       0
Bank Sta=447,462
XS Rating Curve= 0 ,0
Exp/Cntr=0.3,0.1

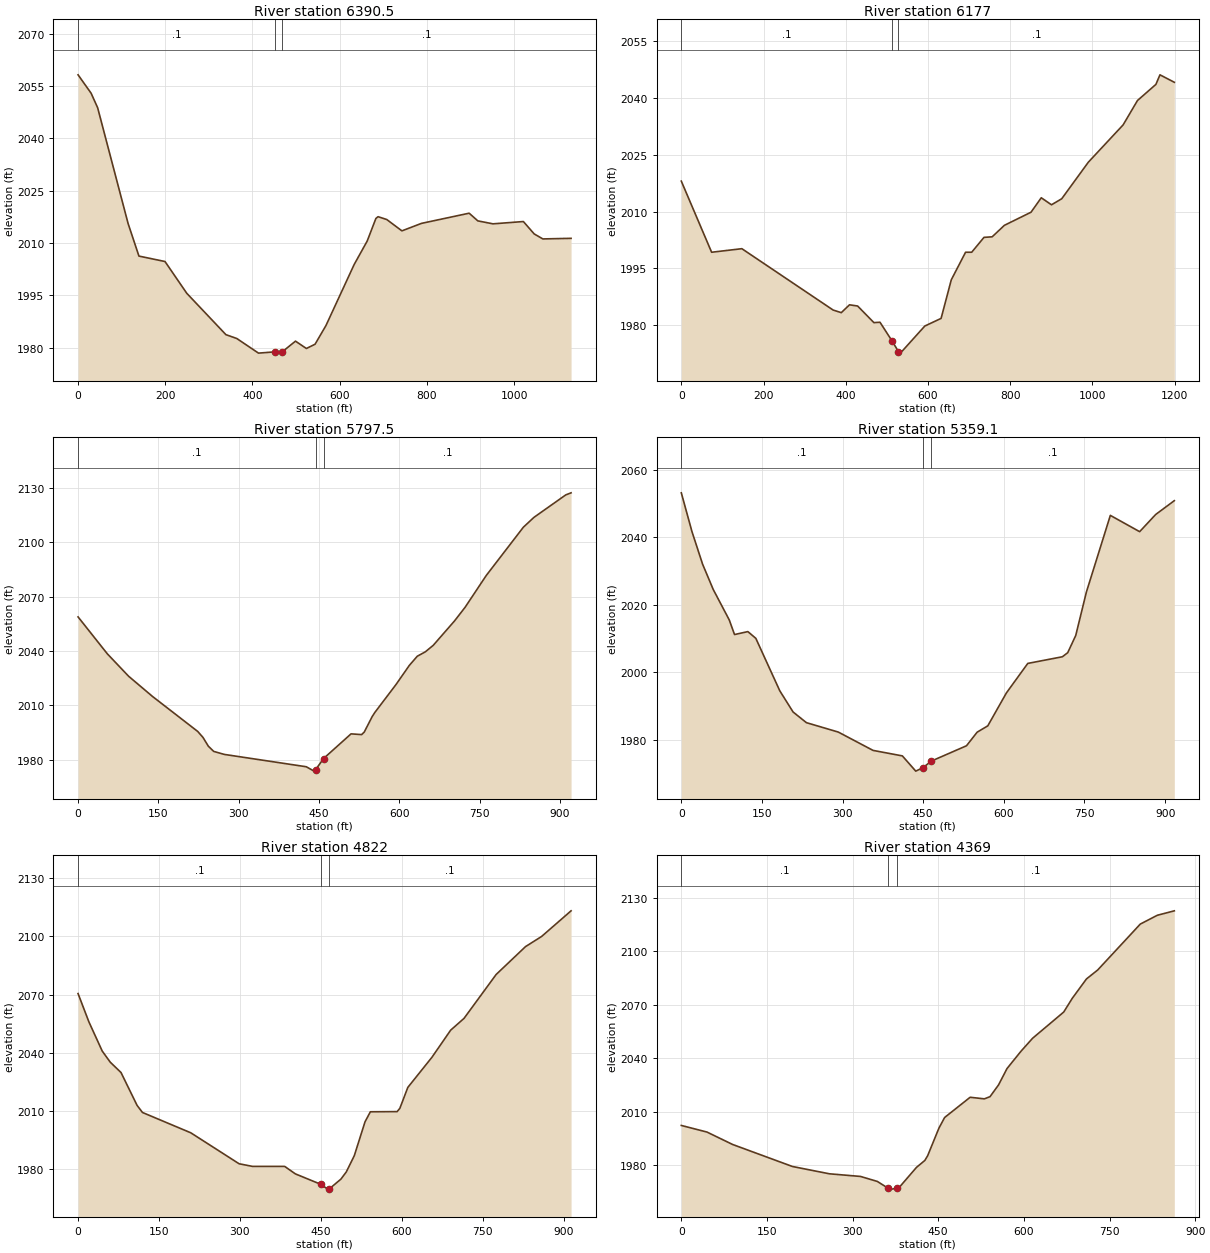
Type RM Length L Ch R = 1 ,6390.5  ,198.8,213.5,226.3
XS GIS Cut Line= 4
     1841009.415      229421.239     1840720.817      229517.208
     1840478.171      229683.884     1840042.979      229990.367
#Sta/Elev= 30
       0 2058.18    29.9 2052.92    44.9 2048.76   114.7 2015.63   139.6 2006.28
   199.4 2004.72   249.3 1995.63   339.1 1983.78     364 1982.68   413.9 1978.49
   452.8 1978.87   467.8 1978.81   498.7 1981.92   523.7 1979.82   543.6 1981.04
   568.6 1986.39   633.3 2003.87   663.2 2010.59   683.1 2017.05   688.1 2017.56
     708 2016.75   742.8  2013.5   787.6 2015.64     897 2018.56   916.9 2016.36
   951.7 2015.51  1021.4 2016.17  1046.2 2012.62  1066.1 2011.19  1130.8 2011.36
#Mann= 3 , 0 , 0
       0      .1       0   452.8    .045       0   467.8      .1       0
Bank Sta=452.8,467.8
XS Rating Curve= 0 ,0
Exp/Cntr=0.3,0.1

Type RM Length L Ch R = 1 ,6177    ,397.3,379.6,361.3
XS GIS Cut Line= 4
     1840960.011      229301.567      1840746.22      229432.056
     1840306.575      229463.823     1839928.186      229802.343
#Sta/Elev= 30
       0 2018.07    73.7 1999.28   147.3 2000.22   369.3    1984   389.1 1983.32
     409 1985.39   428.8 1985.07   468.4 1980.68   483.2 1980.78   512.9 1975.78
   527.9 1973.05   532.8 1972.62   592.2 1979.78   631.8  1981.8   656.6    1992
   691.3 1999.28   706.2 1999.28   736.1 2003.21     756 2003.36   785.8  2006.4
   850.5 2009.86   875.4 2013.68   900.3 2011.82   925.2 2013.42   989.9 2023.08
  1074.5 2032.94  1109.4 2039.38  1154.2 2043.64  1164.1 2046.17    1199  2044.2
#Mann= 3 , 0 , 0
       0      .1       0   512.9    .045       0   527.9      .1       0
Bank Sta=512.9,527.9
XS Rating Curve= 0 ,0
Exp/Cntr=0.3,0.1

Type RM Length L Ch R = 1 ,5797.5  ,434.6,438.4,442.7
XS GIS Cut Line= 4
     1840767.409      228881.288     1840487.229      229078.551
     1840381.684      229188.467     1840001.656      229380.581
#Sta/Elev= 30
       0 2058.81    54.6 2038.44    94.4 2026.03     139 2014.87   223.5 1995.52
   233.4  1992.2   243.3 1987.39   253.3  1984.5   273.1 1982.83   426.2 1976.01
     441 1973.59   443.6 1974.33   458.6 1980.56   509.9 1994.18   529.7 1993.78
   534.6 1995.19   549.5 2003.79   554.5 2006.07   594.1 2021.53   618.8 2032.03
   633.7  2037.1   648.5 2039.48   663.4  2043.1     703 2056.52   722.8 2064.07
   762.4 2081.67   831.7 2108.35   851.6 2113.83     911 2126.24   920.9 2127.38
#Mann= 3 , 0 , 0
       0      .1       0   443.6    .045       0   458.6      .1       0
Bank Sta=443.6,458.6
XS Rating Curve= 0 ,0
Exp/Cntr=0.3,0.1

Type RM Length L Ch R = 1 ,5359.1  ,524,537.1,550.2
XS GIS Cut Line= 4
     1840523.483      228545.381      1840265.13      228737.182
     1840093.562      228864.554     1839750.624      229032.006
#Sta/Elev= 30
       0  2053.1    19.8 2041.63    39.6 2031.97    59.4 2024.48    89.1  2015.5
      99 2011.14   123.8 2012.01   138.6 2010.02   183.2 1994.48   207.9 1988.21
   232.7 1985.05   292.1 1982.26   356.6 1976.84   411.2 1975.21   436.1  1970.7
   449.7 1971.72   464.7 1973.64   530.5 1978.21   550.3 1982.23   570.1  1984.1
   604.8 1993.87   644.5 2002.59   708.9 2004.56   718.8 2005.77   733.7 2010.85
   753.5  2023.7   798.1 2046.42   852.6  2041.6   882.4 2046.68   917.1 2050.78
#Mann= 3 , 0 , 0
       0      .1       0   449.7    .045       0   464.7      .1       0
Bank Sta=449.7,464.7
XS Rating Curve= 0 ,0
Exp/Cntr=0.3,0.1

Type RM Length L Ch R = 1 ,4822    ,468.5,453,437.5
XS GIS Cut Line= 4
     1840385.315       228221.73     1840053.793      228328.288
     1839880.525      228341.312     1839494.273      228406.796
#Sta/Elev= 30
       0 2070.51    19.9 2056.05    44.8 2040.89    59.7 2035.16    79.6 2029.84
   109.4 2012.91   119.4 2009.26   208.9  1998.8   298.5 1982.84   323.4 1981.49
     383 1981.48   402.8 1977.63   450.7 1972.17   462.4 1969.78   465.7 1969.91
   487.2 1974.93   497.2 1978.66     512 1987.01   531.9 2004.47   541.8 2009.62
   591.4 2009.71   596.4 2011.38   611.2 2022.17   655.9 2037.69   690.6 2051.65
   715.4 2057.74   774.9 2080.33   829.4  2094.7   859.2 2099.93   913.8 2113.13
#Mann= 3 , 0 , 0
       0      .1       0   450.7    .045       0   465.7      .1       0
Bank Sta=450.7,465.7
XS Rating Curve= 0 ,0
Exp/Cntr=0.3,0.1

Type RM Length L Ch R = 1 ,4369    ,59.8,57,54.2
XS GIS Cut Line= 4
     1840169.696      227823.669     1839881.896        227854.3
     1839774.199      227954.309     1839420.575      228193.899
#Sta/Elev= 30
       0 2002.25    44.9 1998.54    89.8 1991.57   194.6  1979.2   259.5 1975.09
   313.9 1973.61   343.3 1970.81   362.6 1966.92   367.8 1966.49   377.6 1966.99
   382.5 1967.76   411.9  1978.7   426.6 1982.62   431.5 1985.27   451.3  2000.8
   461.2 2006.71   505.9 2018.07   530.8 2017.18   540.7 2018.41   555.6 2024.99
   570.5 2034.21   595.3 2044.05   615.2 2051.18   669.8 2065.93   684.7 2073.61
   709.6  2084.5   729.4 2089.57   803.9 2115.32   833.7 2120.26   863.5 2122.76
#Mann= 3 , 0 , 0
       0      .1       0   362.6    .045       0   377.6      .1       0
Bank Sta=362.6,377.6
XS Rating Curve= 0 ,0
Exp/Cntr=0.3,0.1

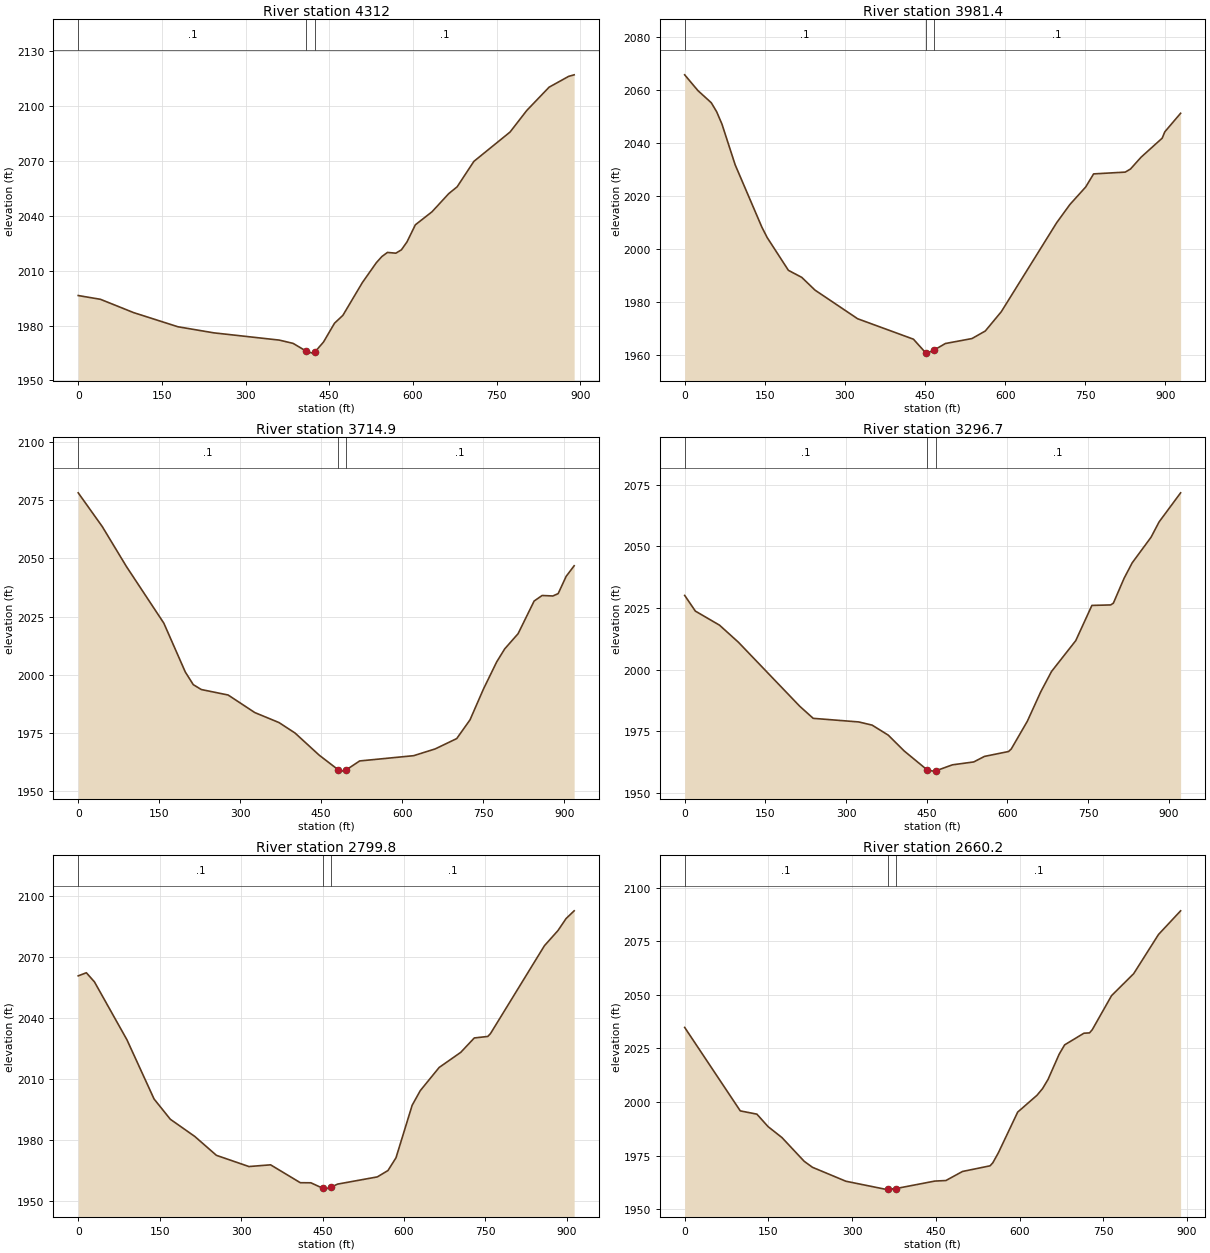
Type RM Length L Ch R = 1 ,4312    ,335.1,330.6,326.1
XS GIS Cut Line= 6
      1840152.23      227796.711     1839995.627      227824.346
     1839897.366      227836.629     1839827.552      227816.561
     1839748.439       227911.86     1839395.314      228165.188
#Sta/Elev= 30
       0 1996.44    39.8 1994.38    99.4 1987.09   178.8 1979.35   243.2 1976.02
   360.4 1972.06   385.2 1970.27   409.1 1965.95   419.9 1964.93   424.1 1965.49
   439.7 1970.98   459.5  1981.3   474.5  1985.6   509.5 2003.57   534.5 2014.41
   544.5  2017.8   554.4 2020.02   569.4 2019.61   579.4 2021.44   589.4 2025.76
   604.4 2035.12   634.4  2042.3   664.4 2052.23   679.3 2055.91   709.3 2069.83
   774.2 2085.89   804.2 2097.71   844.2 2110.43   879.2 2116.34   889.1 2117.19
#Mann= 3 , 0 , 0
       0      .1       0   409.1    .045       0   424.1      .1       0
Bank Sta=409.1,424.1
XS Rating Curve= 0 ,0
Exp/Cntr=0.3,0.1

Type RM Length L Ch R = 1 ,3981.4  ,248.5,266.5,284.4
XS GIS Cut Line= 4
      1839852.94      227378.064     1839545.265      227623.337
     1839446.706      227802.194     1839226.588      228049.156
#Sta/Elev= 30
       0 2065.58    24.9 2059.62    49.8 2055.07    59.8  2051.7    69.7 2047.07
    94.6 2031.64   144.4 2008.25   154.4  2004.3   194.2 1991.93   219.2 1989.28
     244 1984.48   323.8 1973.69   428.3 1965.99   451.2 1960.86   453.2 1960.74
   466.2 1961.81   488.1 1964.36   537.9 1966.23   562.8 1969.07   592.7 1976.32
   696.4 2009.85   721.1  2016.7   750.8 2023.33   765.6 2028.26   824.8 2028.93
   834.7  2030.1   854.4 2034.54     894 2041.72   898.9 2044.11   928.5  2051.1
#Mann= 3 , 0 , 0
       0      .1       0   451.2    .045       0   466.2      .1       0
Bank Sta=451.2,466.2
XS Rating Curve= 0 ,0
Exp/Cntr=0.3,0.1

Type RM Length L Ch R = 1 ,3714.9  ,416.1,418.2,420.7
XS GIS Cut Line= 4
     1839695.457       227225.95     1839378.702      227496.177
     1839119.213      227569.549     1838916.991      227684.082
#Sta/Elev= 30
       0 2078.15    44.6 2063.64    89.2 2046.53   158.6 2022.16   198.3 2001.21
   213.1 1995.76     228 1993.67   277.6 1991.32   327.1 1983.77   371.8 1979.49
   401.5    1975   446.3 1965.48   481.4 1959.23   491.3 1958.63   496.4 1959.18
   521.2    1963   621.1 1965.26     661 1968.16   700.9  1972.6   725.6 1980.67
   750.3 1993.81     775 2005.56   789.9 2011.16   814.6 2017.66   844.3 2031.68
   859.1 2034.06   878.9 2033.85   888.8 2034.86   903.6 2042.28   918.4 2046.82
#Mann= 3 , 0 , 0
       0      .1       0   481.4    .045       0   496.4      .1       0
Bank Sta=481.4,496.4
XS Rating Curve= 0 ,0
Exp/Cntr=0.3,0.1

Type RM Length L Ch R = 1 ,3296.7  ,508,496.9,485.7
XS GIS Cut Line= 4
     1839546.165      226994.822     1839157.139      227148.084
     1838981.416      227181.211     1838694.346      227333.255
#Sta/Elev= 30
       0 2030.05    19.9 2023.68    64.7 2017.99    99.6 2011.12     214 1985.07
   238.9 1980.19   323.6 1978.73   348.4 1977.44   378.3 1973.39   408.2 1966.92
   451.2  1959.2   462.8 1958.78   466.2 1958.85   497.6 1961.33   537.3 1962.51
   557.2 1964.75   601.9 1966.73   606.9 1967.72   636.9 1979.02   661.9 1990.98
   681.9 1999.21   726.9 2011.71   756.9 2025.99   791.8 2026.19   796.8 2026.91
   816.8 2037.03   831.8 2043.27   866.8 2053.64   881.8 2059.86   921.8 2071.66
#Mann= 3 , 0 , 0
       0      .1       0   451.2    .045       0   466.2      .1       0
Bank Sta=451.2,466.2
XS Rating Curve= 0 ,0
Exp/Cntr=0.3,0.1

Type RM Length L Ch R = 1 ,2799.8  ,135.4,139.7,143.6
XS GIS Cut Line= 4
     1839226.389      226438.144     1838930.958      226706.588
      1838791.72      226814.347     1838547.258      227047.888
#Sta/Elev= 30
       0 2060.67      15  2062.2    29.9 2057.72    89.8 2029.26   139.7 2000.22
   169.6 1990.28   214.6 1981.85   254.5 1972.56   314.4 1967.06   354.3  1967.9
     409 1959.12   428.5 1959.08   449.9 1956.45     453 1955.97   464.9 1956.77
   477.4 1958.42   550.8 1961.97   570.4 1965.09   585.2 1971.35     615 1997.16
   629.9 2004.31   664.7  2015.7   704.5 2023.13   729.4 2030.19   754.2 2030.92
   759.2 2032.32   858.6 2075.48   883.5 2082.91   898.4 2088.79   913.3  2092.6
#Mann= 3 , 0 , 0
       0      .1       0   449.9    .045       0   464.9      .1       0
Bank Sta=449.9,464.9
XS Rating Curve= 0 ,0
Exp/Cntr=0.3,0.1

Type RM Length L Ch R = 1 ,2660.2  ,150.6,152.7,154.7
XS GIS Cut Line= 3
     1839165.916      226438.446     1838757.409      226656.432
     1838486.215      226984.268
#Sta/Elev= 30
       0 2034.79    99.6 1995.87   129.4 1994.34   149.4 1988.53   174.3 1983.42
   214.1 1972.36     229 1969.55   288.8 1963.06   358.5 1959.38   363.6 1959.38
   378.6 1959.65   448.1 1963.13     468 1963.39   497.7 1967.61   547.1 1970.25
   552.1 1971.68     562 1976.33   596.6  1995.3   631.2 2003.15   641.1 2006.23
     651 2010.55   670.8 2022.24   680.7 2026.65   715.3 2032.09   725.2 2032.23
   730.2 2033.72   764.8 2049.62   804.4 2059.85   848.9 2078.13   888.5 2089.16
#Mann= 3 , 0 , 0
       0      .1       0   363.6    .045       0   378.6      .1       0
Bank Sta=363.6,378.6
XS Rating Curve= 0 ,0
Exp/Cntr=0.3,0.1

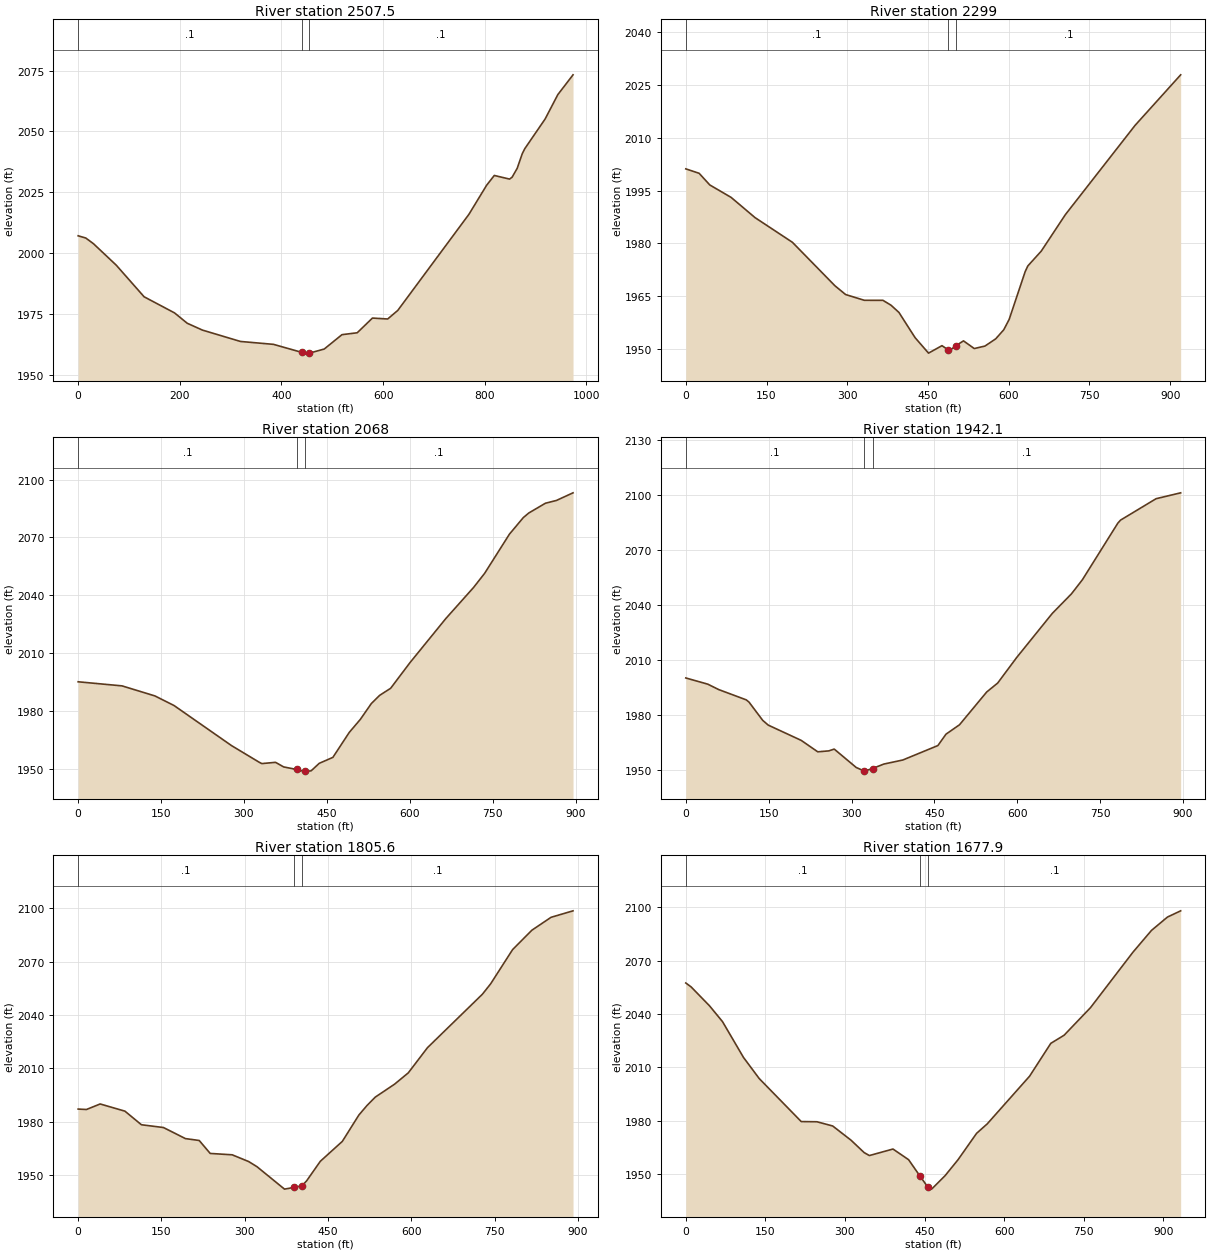
Type RM Length L Ch R = 1 ,2507.5  ,199.3,208.5,217.7
XS GIS Cut Line= 3
     1839133.304      226333.745     1838663.006      226541.431
     1838393.528      226913.894
#Sta/Elev= 30
       0 2007.09      15 2006.17      30 2003.86    74.9 1995.02   129.8    1982
   189.7 1975.37   214.6 1971.12   244.6  1968.3   319.4 1963.63   384.3 1962.44
   440.1 1959.14   454.2 1958.83   455.1 1958.83   484.2 1960.51   519.1 1966.42
   549.1  1967.2   579.1 1973.25   609.1 1972.87     629 1976.41     769 2015.94
   803.9 2027.92   818.9 2031.91   848.9 2030.41   853.9 2031.19   863.9 2034.83
   873.9 2040.86   878.9 2042.93   918.9 2055.14   943.9 2065.16   973.8  2073.3
#Mann= 3 , 0 , 0
       0      .1       0   440.1    .045       0   455.1      .1       0
Bank Sta=440.1,455.1
XS Rating Curve= 0 ,0
Exp/Cntr=0.3,0.1

Type RM Length L Ch R = 1 ,2299    ,238.6,231,229.1
XS GIS Cut Line= 4
     1839086.934      226225.855       1838709.4      226345.478
     1838564.444      226345.478     1838187.935      226384.054
#Sta/Elev= 30
       0 2001.19    24.8 1999.93    44.6 1996.62    84.2 1993.09   128.7 1987.34
     198 1980.35   277.2 1967.98     297  1965.5   331.7 1963.87   366.3 1963.86
   381.2 1962.49     396 1960.43     426 1953.27     451 1948.87     476 1950.99
   487.1 1949.84     491  1949.7   502.1    1951     516 1952.35     536 1950.17
   555.9 1950.88   575.8 1952.92   590.8  1955.5   600.8 1958.43   630.6 1972.02
   635.6 1973.64   660.5 1977.84   705.3  1988.2   834.8 2013.54   919.5 2027.89
#Mann= 3 , 0 , 0
       0      .1       0   487.1    .045       0   502.1      .1       0
Bank Sta=487.1,502.1
XS Rating Curve= 0 ,0
Exp/Cntr=0.3,0.1

Type RM Length L Ch R = 1 ,2068    ,126.4,125.9,123.6
XS GIS Cut Line= 4
     1839054.194       226055.13     1838679.576        226129.1
     1838565.954       226129.09     1838171.226      226193.033
#Sta/Elev= 30
       0 1995.16    79.4 1993.04   138.9 1987.83   173.6 1982.84   277.7 1962.04
   327.3  1953.5   332.3 1952.76   357.1 1953.41   371.9 1951.02   395.2 1949.72
   406.6 1948.85   410.2 1948.87   421.4 1948.97   436.2 1952.89   460.9 1955.98
   490.5 1968.91   510.5 1975.65   530.5 1983.89   545.5 1988.13   565.4 1991.79
   600.4 2005.09   665.4 2027.99   715.4 2044.04   735.4 2051.35   780.4 2071.71
   805.4 2080.26   815.4 2082.66   845.4 2087.71   865.4 2089.16   895.4 2093.11
#Mann= 3 , 0 , 0
       0      .1       0   395.2    .045       0   410.2      .1       0
Bank Sta=395.2,410.2
XS Rating Curve= 0 ,0
Exp/Cntr=0.3,0.1

Type RM Length L Ch R = 1 ,1942.1  ,134.8,136.5,138.3
XS GIS Cut Line= 4
     1839038.277      225962.177      1838665.15      226023.918
     1838543.011      226022.576     1838159.147      226117.871
#Sta/Elev= 30
       0 2000.19    39.8 1996.81    59.7 1993.85   109.5 1988.26   114.5 1987.02
   139.3 1977.07   149.3  1974.5     209 1966.18   238.9 1959.96   258.8 1960.46
   268.7 1961.45   308.5 1951.43     323 1949.49   323.5 1949.44     338 1950.85
   358.3 1953.27   392.9  1955.5   456.4 1963.37     471 1969.56   495.5 1974.69
   544.8 1992.56   564.6 1997.41   599.2  2011.4   663.5 2035.36   698.1 2045.98
   717.9 2053.65   782.2 2084.55   787.1 2086.18   851.4 2097.84   895.9 2101.04
#Mann= 3 , 0 , 0
       0      .1       0     323    .045       0     338      .1       0
Bank Sta=323,338
XS Rating Curve= 0 ,0
Exp/Cntr=0.3,0.1

Type RM Length L Ch R = 1 ,1805.6  ,143.3,127.6,112
XS GIS Cut Line= 4
     1839016.802      225856.145     1838664.656      225912.825
     1838561.129      225925.363     1838149.338       226050.02
#Sta/Elev= 30
       0    1987    14.9 1986.75    39.6 1989.87    84.2 1985.83   113.9 1978.18
   153.6 1976.61   193.2 1970.38     218 1969.32   237.8 1962.03   277.4 1961.26
   307.1 1957.46     322 1954.58   371.6 1941.95     388 1942.88     403 1943.83
   411.3 1946.55   436.1 1957.61   475.8 1968.84   505.5 1983.63   520.3 1989.05
   535.1 1993.73   569.8    2001   594.5 2007.37   629.1 2021.55     728 2051.63
   742.8 2057.46   782.4 2076.74     817 2087.62   851.6  2094.9   891.2 2098.55
#Mann= 3 , 0 , 0
       0      .1       0     388    .045       0     403      .1       0
Bank Sta=388,403
XS Rating Curve= 0 ,0
Exp/Cntr=0.3,0.1

Type RM Length L Ch R = 1 ,1677.9  ,102.8,105.6,108.4
XS GIS Cut Line= 4
     1838957.688      225606.826     1838606.158      225765.476
     1838521.066      225846.664     1838129.232      226022.763
#Sta/Elev= 30
       0 2057.42     9.9 2055.25    44.5 2044.65    69.2 2035.69   108.8 2015.53
   138.4 2003.67   217.6 1979.47   247.2 1979.36   276.9 1976.99   311.5 1968.99
   336.2 1962.02   346.1 1960.36   390.6 1964.02     420 1958.03   441.3 1948.87
   456.3 1942.61   459.2 1941.47   464.1 1941.66   488.6 1948.97   513.3 1958.05
   548.2 1972.86   568.2 1978.16   648.1    2005   688.1 2023.47   713.1 2028.02
     763 2043.58     843 2074.76   877.9    2087   907.9 2094.48   932.9 2098.01
#Mann= 3 , 0 , 0
       0      .1       0   441.3    .045       0   456.3      .1       0
Bank Sta=441.3,456.3
XS Rating Curve= 0 ,0
Exp/Cntr=0.3,0.1