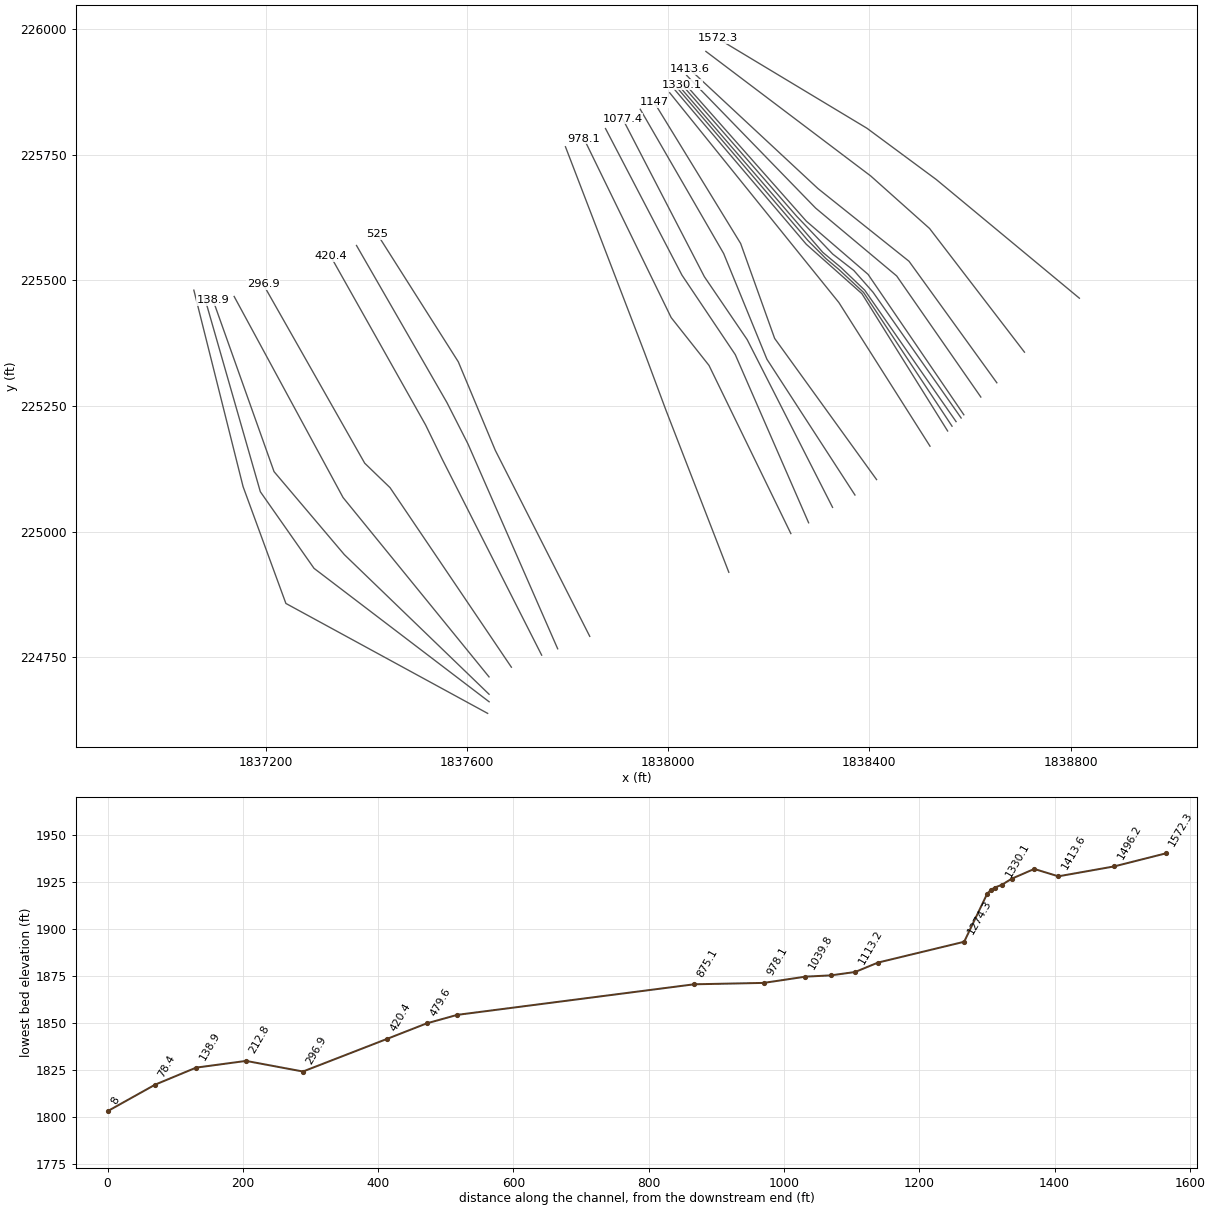
HEC-RAS study BlackFk.prj: BlackFk

--- BlackFk.g01 (geometry) --- (continued)

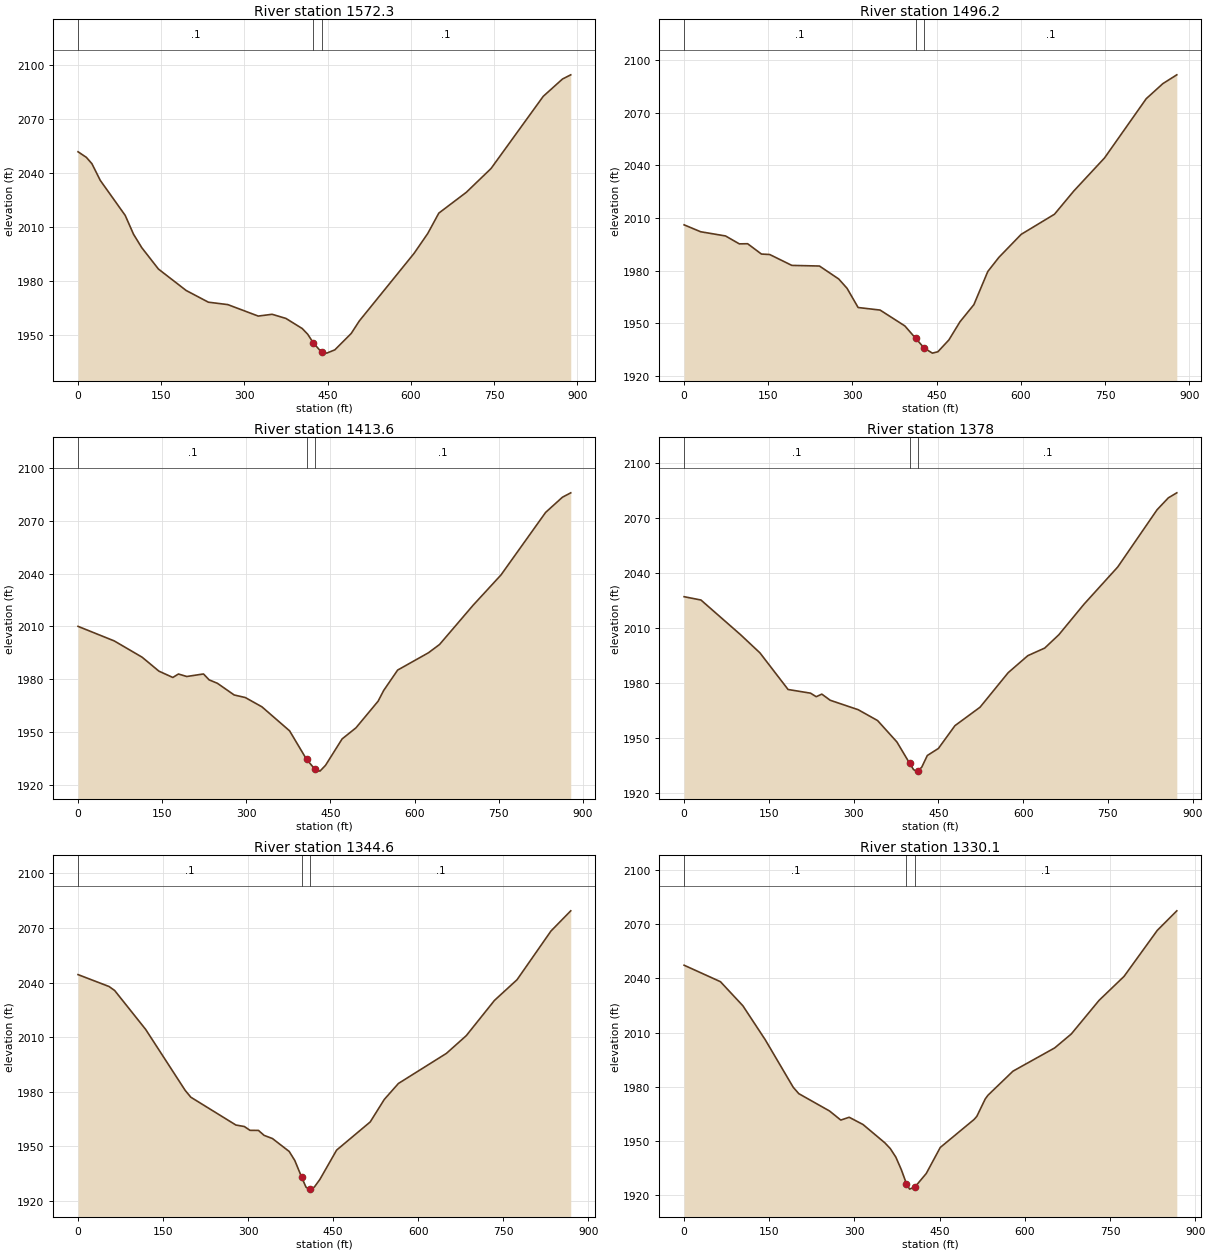
Type RM Length L Ch R = 1 ,1572.3  ,78.2,76.1,74.1
XS GIS Cut Line= 4
     1838817.444      225464.722     1838532.901      225700.946
     1838395.103      225802.952     1838098.033       225981.91
#Sta/Elev= 30
       0 2051.93      15 2048.83      25  2045.3      40 2036.06      85 2016.56
     100 2006.09   114.9  1998.6   144.9 1986.73   194.9 1974.81   234.9 1968.31
   269.9 1966.97   324.8 1960.59   349.8 1961.58   374.7 1959.28   404.1 1953.66
   413.9 1950.52   424.2 1945.63   439.2 1940.41   448.2 1939.99   462.9 1941.82
   492.3  1950.9     507 1957.88   605.7 1995.46   630.4 2006.53   650.3 2017.83
   699.8 2029.38   744.4 2042.62   838.5 2082.75   873.2 2092.38   888.1 2094.71
#Mann= 3 , 0 , 0
       0      .1       0   424.2    .045       0   439.2      .1       0
Bank Sta=424.2,439.2
XS Rating Curve= 0 ,0
Exp/Cntr=0.3,0.1

Type RM Length L Ch R = 1 ,1496.2  ,81.3,82.6,83.8
XS GIS Cut Line= 4
      1838708.28      225357.347     1838519.619      225603.465
     1838402.702      225707.909     1838074.853      225955.919
#Sta/Elev= 30
       0 2006.16    29.5 2002.22    73.8 1999.83    98.4 1995.32   113.2  1995.4
   137.8 1989.52   152.6 1989.25     192 1983.06   241.2  1982.7   275.6  1975.3
   290.4    1970   310.1 1959.07   349.3 1957.61   393.4 1948.58   412.9 1941.43
   427.9 1935.96   442.4 1933.09   452.2 1933.86   471.8 1940.58   491.6 1950.94
   516.4 1960.71   541.2 1979.58     561 1987.65   600.6 2000.72     660  2012.2
   694.7 2025.52   749.2 2044.26   823.5    2078   853.2  2086.6     878  2091.6
#Mann= 3 , 0 , 0
       0      .1       0   412.9    .045       0   427.9      .1       0
Bank Sta=412.9,427.9
XS Rating Curve= 0 ,0
Exp/Cntr=0.3,0.1

Type RM Length L Ch R = 1 ,1413.6  ,36.1,35.6,35.1
XS GIS Cut Line= 4
     1838653.334      225296.404     1838478.726      225538.247
     1838297.655      225682.952     1838042.641      225920.519
#Sta/Elev= 30
       0 2010.06    64.6 2001.78   114.3 1992.53   144.2 1984.62     169 1981.03
     179 1982.99   193.9 1981.58   223.7 1983.02   233.7 1979.68   248.6  1977.7
   278.4 1971.08   298.3 1969.62   327.9 1964.35   377.2 1950.72   407.5 1934.52
   422.5 1928.88   431.4 1927.82   441.3 1931.12   470.9 1946.12   495.6 1952.42
   535.1 1967.56     545 1973.64   569.9 1985.22   624.7 1995.03   644.6 1999.75
   704.3 2021.99   754.1 2039.23   833.8  2074.8   863.7 2083.41   878.6 2085.92
#Mann= 3 , 0 , 0
       0      .1       0   407.5    .045       0   422.5      .1       0
Bank Sta=407.5,422.5
XS Rating Curve= 0 ,0
Exp/Cntr=0.3,0.1

Type RM Length L Ch R = 1 ,1378    ,33.7,33.4,33.1
XS GIS Cut Line= 4
     1838621.511       225268.03      1838454.16      225509.076
     1838292.951      225644.185     1838036.552      225908.261
#Sta/Elev= 30
       0  2026.9    29.8  2025.1    99.5 2006.29   134.3 1996.23     184 1976.28
   223.8 1974.27   233.8 1972.34   243.7 1973.75   258.6  1970.4   308.1 1965.25
   342.4 1959.33   376.6 1947.65     399 1936.05     406  1932.6   410.8 1931.74
     414 1931.98   420.6 1933.92   430.4 1940.27     450 1944.11   479.3 1956.55
   523.7 1966.61   573.4 1985.42   608.2 1994.73   638.1 1998.87     663  2006.1
   707.7 2022.82   767.4 2043.13     837 2074.35   856.9 2080.84   871.9 2083.58
#Mann= 3 , 0 , 0
       0      .1       0     399    .045       0     414      .1       0
Bank Sta=399,414
XS Rating Curve= 0 ,0
Exp/Cntr=0.3,0.1

Type RM Length L Ch R = 1 ,1344.6  ,13.4,14.5,14.9
XS GIS Cut Line= 4
     1838587.734      225232.718     1838397.353      225512.147
     1838274.527      225618.084     1838030.411      225894.443
#Sta/Elev= 30
       0 2044.35    54.7 2037.81    64.6 2035.62   119.3 2014.24     189 1980.77
   198.9 1977.03   278.4 1961.75   293.4 1960.91   303.3 1958.83   318.2 1958.79
   328.2 1956.06     343 1954.31   372.5 1947.22   382.4 1942.23   394.6 1932.97
     402 1927.68   406.9 1926.54   409.6 1926.67   416.8 1927.67   426.6 1931.88
   456.1 1947.97   515.3 1963.42   540.2  1975.8   565.1 1984.56   649.8 2001.09
   684.7 2010.79   734.5 2030.17   774.4 2041.56   834.2 2068.28   869.1 2079.38
#Mann= 3 , 0 , 0
       0      .1       0   394.6    .045       0   409.6      .1       0
Bank Sta=394.6,409.6
XS Rating Curve= 0 ,0
Exp/Cntr=0.3,0.1

Type RM Length L Ch R = 1 ,1330.1  ,12.2,10.6,10.7
XS GIS Cut Line= 6
     1838582.371      225226.294     1838407.239      225476.574
     1838369.029       225519.88     1838327.039      225552.575
     1838255.304      225627.937     1838027.204      225889.688
#Sta/Elev= 30
       0 2047.34      64 2038.22   103.5 2024.88   142.9 2006.05   192.2 1979.71
     202 1976.19   256.2 1966.58   275.9 1961.56   290.7 1963.12   315.1  1959.1
   353.6 1948.94   363.2 1945.74   372.9 1941.02   382.6 1934.06   391.6  1926.3
   397.1 1923.31   406.6 1924.54   426.4 1931.95   451.1 1946.38   510.6 1961.88
   515.5 1963.63   530.3 1973.25   535.2 1975.34   579.2 1988.66   652.6 2001.52
   681.9 2009.26   730.8 2027.87   774.8 2041.16   833.4 2066.67   867.7 2077.47
#Mann= 3 , 0 , 0
       0      .1       0   391.6    .045       0   406.6      .1       0
Bank Sta=391.6,406.6
XS Rating Curve= 0 ,0
Exp/Cntr=0.3,0.1

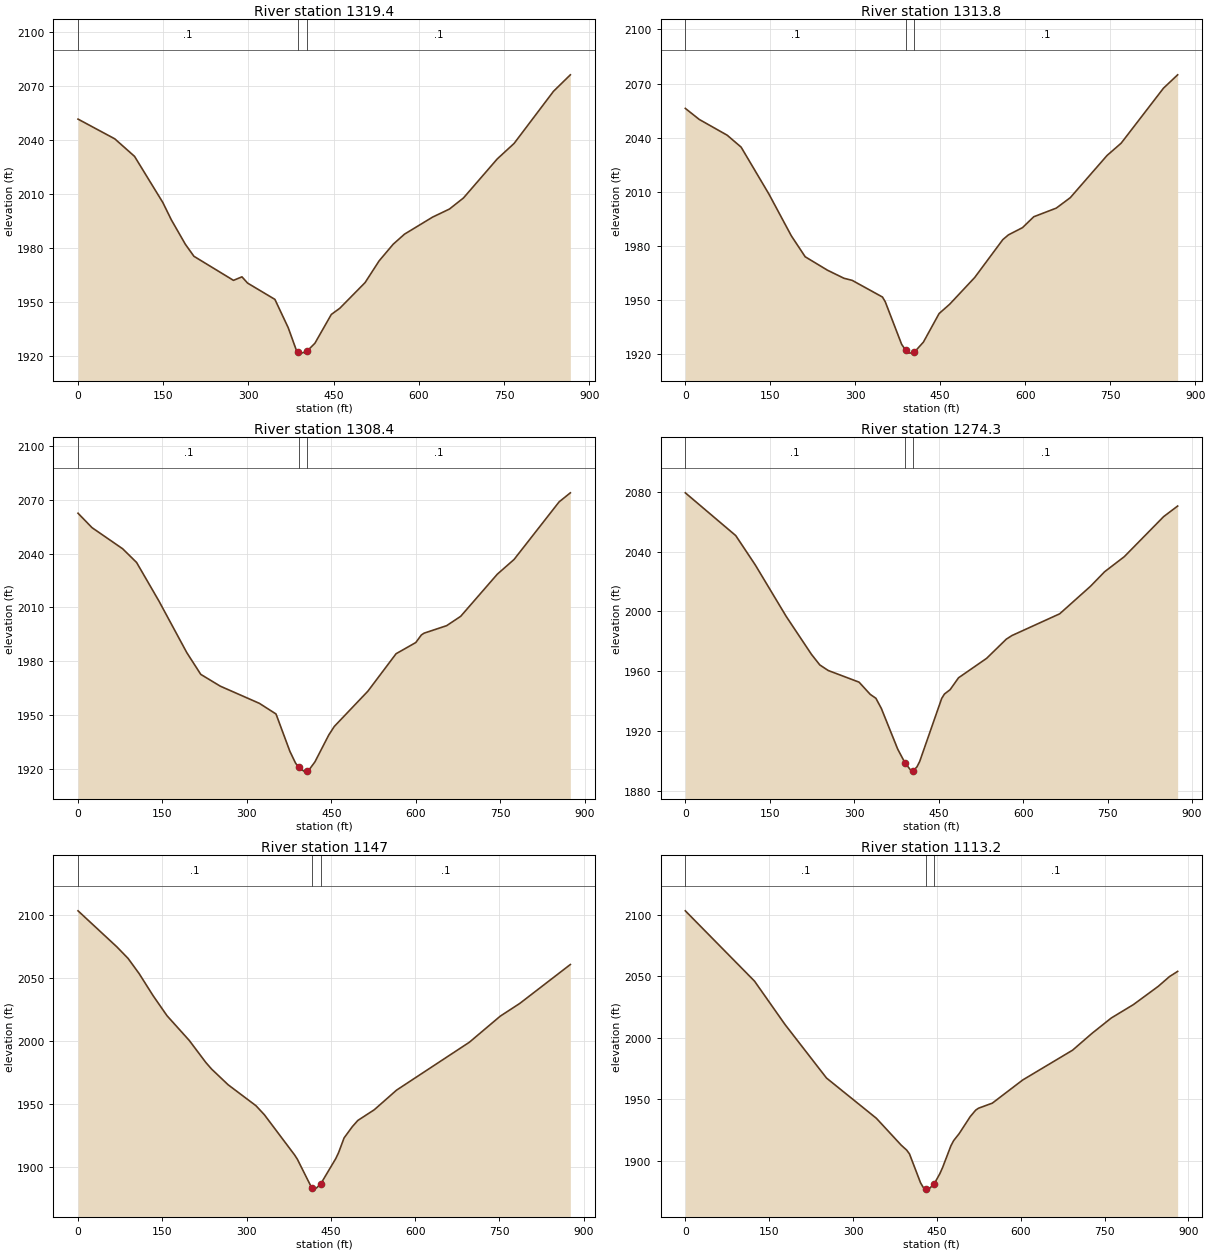
Type RM Length L Ch R = 1 ,1319.4  ,5.6,5.6,5.6
XS GIS Cut Line= 5
     1838572.308      225219.116     1838390.718      225480.625
     1838343.223      225526.045     1838307.237         225556.
     1838022.574      225885.751
#Sta/Elev= 30
       0 2051.49    64.7 2040.56    99.5 2030.84   149.2 2005.32   164.2 1995.71
     189 1982.11     204  1975.5   273.6 1962.17   288.5 1964.12   298.5 1960.64
   346.5 1951.63     370  1935.9   384.1 1923.61   387.7 1922.59   393.5 1921.86
   402.7 1922.85   416.9 1927.33   445.8  1943.3   460.6 1946.67   505.2 1960.92
   529.9 1972.95   554.7 1982.19   574.5 1987.74     624  1997.2   653.7 2001.67
   678.4 2007.81   737.8 2029.42   767.5 2038.02   836.8 2066.88   866.5 2076.02
#Mann= 3 , 0 , 0
       0      .1       0   387.7    .045       0   402.7      .1       0
Bank Sta=387.7,402.7
XS Rating Curve= 0 ,0
Exp/Cntr=0.3,0.1

Type RM Length L Ch R = 1 ,1313.8  ,5.4,5.4,4.7
XS GIS Cut Line= 6
     1838564.274      225210.023     1838388.385      225476.184
     1838338.888      225522.328     1838313.158      225543.889
     1838277.335      225580.069     1838018.697      225882.411
#Sta/Elev= 30
       0 2056.23    24.6 2050.11    73.9 2041.37    98.5 2034.76   147.7 2008.69
   187.1 1985.63   211.6 1974.01   250.7  1966.6     280  1962.1   294.6 1960.93
     348  1951.7   352.9 1949.11   381.9 1925.46   389.1 1922.23   396.3 1920.61
   404.1 1921.07   420.3 1926.72     448 1942.54   466.6 1947.69   510.9 1962.54
   560.5 1983.52   570.4 1986.14   595.3 1990.16   615.1 1996.18   654.8 2000.96
   679.6 2006.76   744.4 2030.11   769.4 2036.96   844.1 2067.43   869.1 2074.83
#Mann= 3 , 0 , 0
       0      .1       0   389.1    .045       0   404.1      .1       0
Bank Sta=389.1,404.1
XS Rating Curve= 0 ,0
Exp/Cntr=0.3,0.1

Type RM Length L Ch R = 1 ,1308.4  ,37.9,34.1,30.3
XS GIS Cut Line= 4
     1838555.492      225200.476     1838385.071      225473.764
     1838274.527      225572.025     1838012.682      225880.073
#Sta/Elev= 30
       0 2062.47    24.8 2054.43    79.3 2042.63     104    2035   143.7 2013.48
   193.2 1984.69     218 1972.58   252.7    1966   322.1 1956.42   351.6 1950.49
   376.3  1929.6   386.2 1923.15   392.1 1920.66     401 1918.62   407.1 1918.87
   410.8 1919.57   420.7 1923.78   445.3 1938.79   455.2 1943.58   514.9 1963.27
   564.8  1984.1   599.8 1990.34   609.7 1994.57   614.7 1995.59   654.6 1999.75
   679.6 2004.98   744.5 2028.44   774.4  2036.7   854.3 2068.79   874.3 2073.85
#Mann= 3 , 0 , 0
       0      .1       0   392.1    .045       0   407.1      .1       0
Bank Sta=392.1,407.1
XS Rating Curve= 0 ,0
Exp/Cntr=0.3,0.1

Type RM Length L Ch R = 1 ,1274.3  ,135.1,127.4,119.6
XS GIS Cut Line= 4
     1838520.458      225170.238     1838339.263      225456.123
     1838272.154      225539.339     1838002.966      225873.588
#Sta/Elev= 30
       0 2079.43    89.6 2050.78   124.4 2031.06   179.2 1996.67     224  1971.3
   238.9 1964.18   253.8 1960.46   308.6 1952.65   328.5 1944.45   338.5 1941.86
   348.2 1935.05   377.3 1907.77     390 1898.76   401.6 1893.07     405 1893.44
   411.4 1895.91   416.2 1899.43   455.4 1941.77   460.3 1944.72   470.3  1947.6
   485.3 1955.57   535.2  1968.6   570.1 1981.42   580.1 1983.85     665 1998.42
   719.8 2016.89   744.8 2026.59   779.7 2036.66   849.6 2063.49   874.5 2070.58
#Mann= 3 , 0 , 0
       0      .1       0     390    .045       0     405      .1       0
Bank Sta=390,405
XS Rating Curve= 0 ,0
Exp/Cntr=0.3,0.1

Type RM Length L Ch R = 1 ,1147    ,32.8,33.8,34.8
XS GIS Cut Line= 4
     1838414.242       225103.75     1838211.579      225384.715
     1838144.025       225573.56     1837972.068      225854.524
#Sta/Elev= 30
       0 2103.63    69.3 2074.86    89.1 2065.73   108.9 2053.56   133.6 2036.09
   158.4 2020.11     198 2000.42   227.6 1982.82   237.6 1977.69   267.2 1965.12
   316.7 1948.46   331.6 1941.32   385.6 1909.19   390.5  1905.8   414.9    1884
   417.3 1883.03   419.8 1882.02   424.7 1883.02   432.3  1886.4   458.9 1906.41
   463.8 1911.04   473.6 1922.78   488.3 1931.77   498.1 1936.71   527.4 1945.24
     567 1960.84   696.7    1999   751.6 2019.75   786.6 2029.96   876.4 2060.88
#Mann= 3 , 0 , 0
       0      .1       0   417.3    .045       0   432.3      .1       0
Bank Sta=417.3,432.3
XS Rating Curve= 0 ,0
Exp/Cntr=0.3,0.1

Type RM Length L Ch R = 1 ,1113.2  ,30.9,35.8,40.6
XS GIS Cut Line= 4
     1838371.253      225073.044     1838196.226      225343.261
     1838110.248      225553.601     1837944.432      225840.707
#Sta/Elev= 30
       0 2103.19   123.8 2046.05   178.3 2010.83   252.6 1967.28   341.7 1934.62
   386.2 1912.75     396 1908.72     401 1905.64   420.8 1882.13   425.7  1878.4
   430.5 1877.19   435.6 1877.02   445.5 1881.52   455.3 1889.57   460.3 1894.65
   475.1 1912.22     480 1916.44   489.9 1922.15   509.7 1935.98   519.5 1941.24
   524.5 1942.78   549.2  1946.9   603.6 1965.74   692.7 1989.92   727.3 2003.54
     762  2016.1   801.6 2026.99   846.1 2041.85   865.9 2049.68   880.7 2053.97
#Mann= 3 , 0 , 0
       0      .1       0   430.5    .045       0   445.5      .1       0
Bank Sta=430.5,445.5
XS Rating Curve= 0 ,0
Exp/Cntr=0.3,0.1

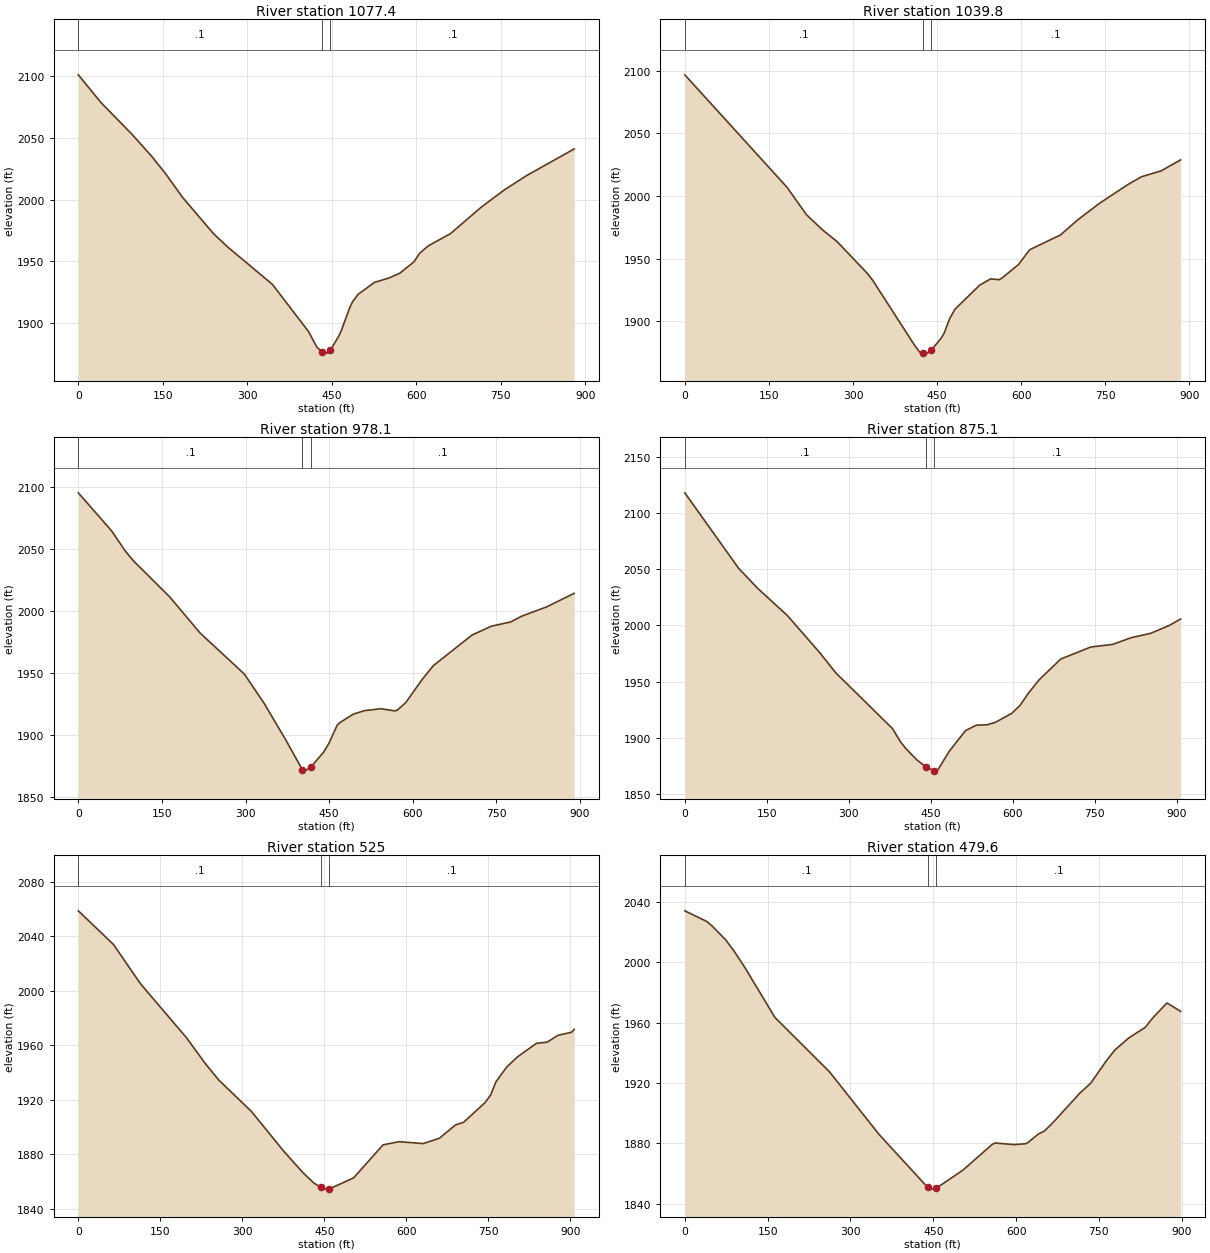
Type RM Length L Ch R = 1 ,1077.4  ,38.4,37.6,36.8
XS GIS Cut Line= 4
     1838326.728      225048.479     1838156.959      225382.321
     1838071.864      225507.541      1837909.12      225822.283
#Sta/Elev= 30
       0 2101.34      40 2078.93    94.9 2053.18   129.8 2035.38   154.8 2021.11
   184.8 2001.94   239.7 1972.42   264.7 1961.64   344.6 1931.06   408.7 1892.74
   423.4 1880.13   432.4 1876.28   442.9 1875.23   447.4 1877.58   462.4 1889.05
   467.3 1894.11     482 1912.37   486.9 1917.07   496.6 1922.95   525.9 1932.74
   550.9 1936.17   570.8  1940.2   595.8 1949.38   605.8 1956.29   620.8 1962.25
   660.7 1972.33   715.6 1993.95   755.5  2007.6   795.4 2019.38   880.2  2041.1
#Mann= 3 , 0 , 0
       0      .1       0   432.4    .045       0   447.4      .1       0
Bank Sta=432.4,447.4
XS Rating Curve= 0 ,0
Exp/Cntr=0.3,0.1

Type RM Length L Ch R = 1 ,1039.8  ,59.3,61.7,64.1
XS GIS Cut Line= 4
     1838279.133      225017.772     1838133.277      225352.473
      1838027.34      225510.612     1837875.343      225802.323
#Sta/Elev= 30
       0 2096.79   182.6 2006.85   217.1 1985.04   246.7 1972.56   271.4 1963.72
   325.6 1938.25   335.5 1932.48     409 1881.41   418.8 1875.38   423.7 1874.55
   424.2 1874.56   433.4 1874.65   439.2 1876.68   457.8  1886.8   462.7 1890.59
   472.5 1902.17   482.2 1909.74   526.2 1928.92   545.7 1933.86   560.4  1933.2
   565.4 1934.35   595.3 1945.33   615.2 1957.13   670.1 1968.91     700 1980.66
   739.8 1994.21   789.7    2009   814.6 2015.41   849.5 2020.08   884.4 2028.88
#Mann= 3 , 0 , 0
       0      .1       0   424.2    .045       0   439.2      .1       0
Bank Sta=424.2,439.2
XS Rating Curve= 0 ,0
Exp/Cntr=0.3,0.1

Type RM Length L Ch R = 1 ,978.1   ,110.2,103,95.8
XS GIS Cut Line= 4
     1838243.821      224996.278     1838081.076      225330.979
     1838005.846      225426.169     1837832.354      225782.364
#Sta/Elev= 30
       0 2095.59    59.6 2064.98    84.4 2048.61    99.2 2040.61   163.8  2011.8
   218.3 1982.65   297.7 1949.58   332.5 1926.54   372.2 1896.44   402.2 1872.19
   406.1 1871.23   417.2 1874.49   440.1 1886.48   449.8 1893.76   464.4 1908.23
   469.2 1910.32   493.5 1917.18   513.3 1919.99     543 1921.53   567.8  1919.8
   572.7 1920.45   587.6 1926.57   617.3 1945.29   637.1 1956.31   706.5 1980.95
   741.1 1988.06   775.8 1991.51   795.6 1996.14   840.2 2003.61   889.7 2014.57
#Mann= 3 , 0 , 0
       0      .1       0   402.2    .045       0   417.2      .1       0
Bank Sta=402.2,417.2
XS Rating Curve= 0 ,0
Exp/Cntr=0.3,0.1

Type RM Length L Ch R = 1 ,875.1   ,349.1,350,350.9
XS GIS Cut Line= 4
     1838120.487       224919.25     1837995.664      225241.374
     1837952.714      225356.802     1837795.679      225766.168
#Sta/Elev= 30
       0 2117.97    98.7 2050.72   133.2 2033.12   187.5 2008.94   246.8 1975.88
   276.4 1957.79     380 1908.31   394.7 1896.47   404.6 1890.46   424.3  1880.6
   440.4 1874.53   455.4 1870.87   458.8 1870.49   463.7 1872.12   483.6 1888.01
   513.5 1906.49   533.4 1911.36   553.3 1911.73   568.3 1913.88   598.2 1921.89
   613.1 1928.85   628.1 1939.42     648  1951.6   687.8 1970.14   742.7 1980.85
   782.5 1983.16   817.4 1989.24   852.3 1993.02   887.2 2000.26   907.1 2005.77
#Mann= 3 , 0 , 0
       0      .1       0   440.4    .045       0   455.4      .1       0
Bank Sta=440.4,455.4
XS Rating Curve= 0 ,0
Exp/Cntr=0.3,0.1

Type RM Length L Ch R = 1 ,525     ,44.9,45.4,47.1
XS GIS Cut Line= 4
     1837843.997      224791.743     1837656.092      225162.185
     1837582.654      225338.137     1837421.702      225592.093
#Sta/Elev= 30
       0 2058.72    64.3 2033.99   113.7 2005.12   197.8 1965.49   232.4 1946.41
   257.1 1934.28   316.5 1911.36   375.8 1882.03   410.4 1866.53     430    1859
   443.3 1855.48   454.5 1854.26   458.3 1854.29   503.4 1862.51   557.2 1886.79
   586.5 1889.12   630.7 1887.72   660.3 1891.65   689.8 1901.44   704.6 1903.37
     744 1917.95   753.9 1923.38   763.8 1933.16   783.5 1944.02   803.2 1951.47
   837.7 1961.36   857.4 1962.24   877.1 1967.26   901.8 1969.52   906.7 1971.67
#Mann= 3 , 0 , 0
       0      .1       0   443.3    .045       0   458.3      .1       0
Bank Sta=443.3,458.3
XS Rating Curve= 0 ,0
Exp/Cntr=0.3,0.1

Type RM Length L Ch R = 1 ,479.6   ,58.2,59.2,58.8
XS GIS Cut Line= 4
     1837780.216      224767.022     1837601.705      225175.046
     1837560.097      225256.919     1837380.245      225569.648
#Sta/Elev= 30
       0 2033.95    39.6 2026.94    49.5 2023.92    74.2 2014.67    89.1 2007.37
   108.9 1996.36   163.3 1963.34   262.3 1927.29   351.3 1886.15     440 1850.82
   450.2 1849.72     455 1850.21   503.4 1862.19     557 1879.41   561.9 1880.23
   596.5 1879.19   616.3 1879.71   621.2 1880.46     641 1886.37   650.9 1888.07
   665.7  1893.3   715.1 1913.13   734.9 1919.73   764.5 1935.16   779.4 1941.99
   804.1 1949.79   833.7 1956.77   848.5 1963.45   873.2 1972.93     898 1967.44
#Mann= 3 , 0 , 0
       0      .1       0     440    .045       0     455      .1       0
Bank Sta=440,455
XS Rating Curve= 0 ,0
Exp/Cntr=0.3,0.1

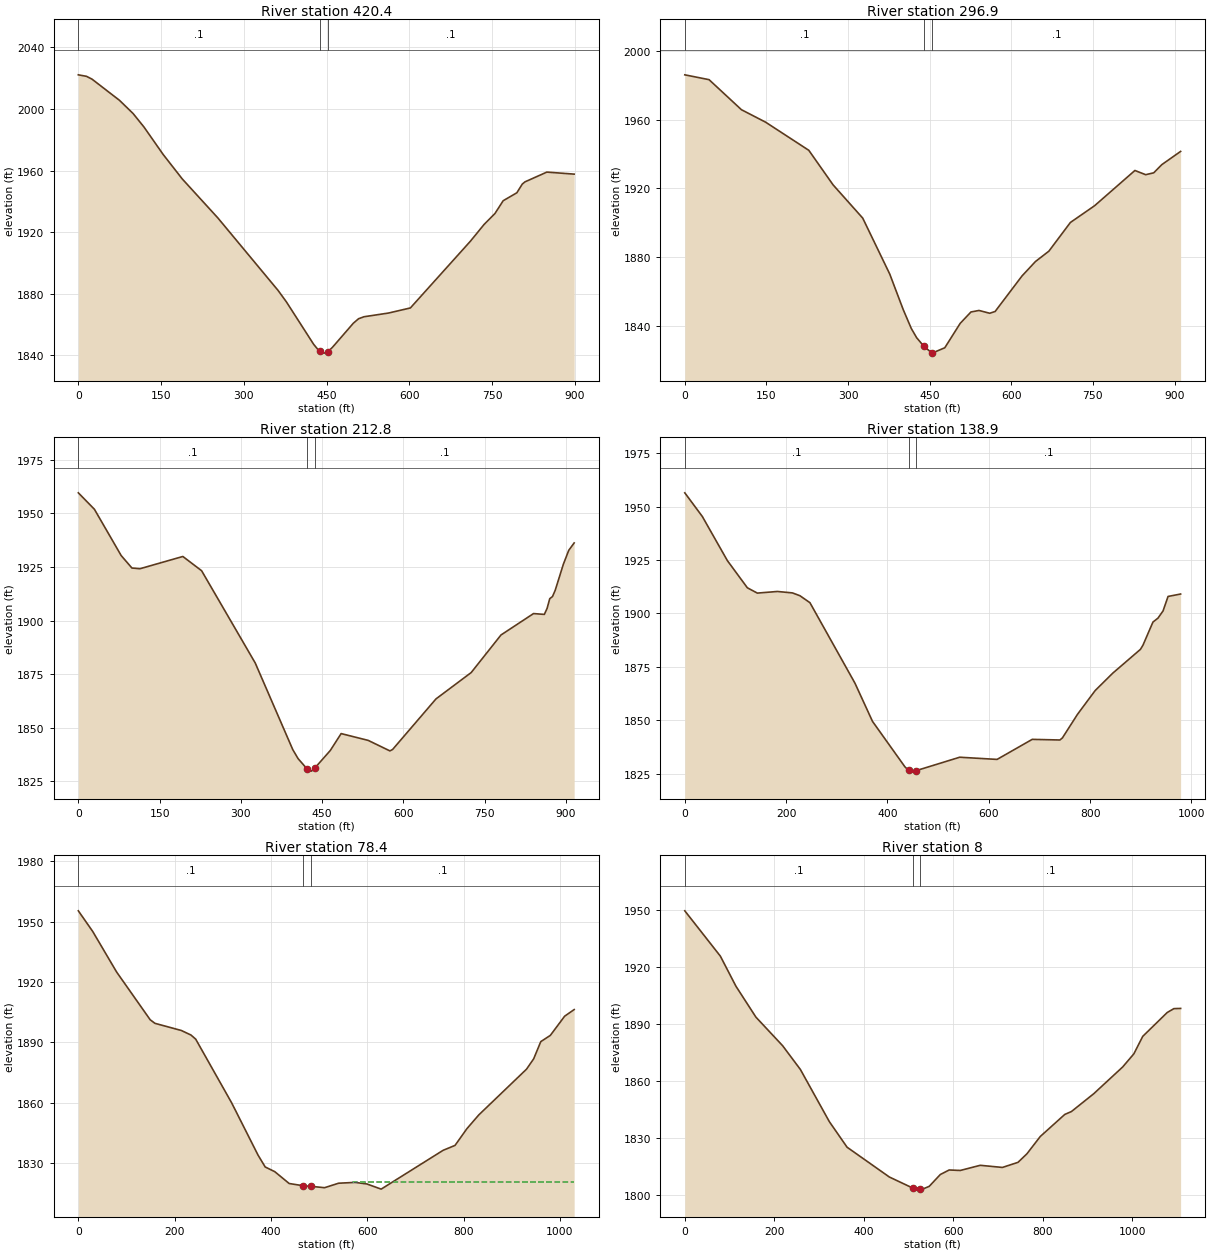
Type RM Length L Ch R = 1 ,420.4   ,117.2,123.5,131.8
XS GIS Cut Line= 4
     1837748.381      224754.334      1837551.08      225143.568
     1837517.756      225212.229     1837328.634      225548.572
#Sta/Elev= 30
       0 2022.24    14.9 2021.25    24.8 2019.43    74.4 2005.73    99.2 1997.11
     119 1988.31   153.7 1970.51   188.4 1954.57   252.9 1929.23     362 1882.14
   376.9 1874.79   426.5 1847.11   437.2 1842.47   445.9 1841.39   452.2 1842.33
   460.2 1845.02   498.4 1860.82   507.9 1863.74   517.6 1865.02   562.2 1867.44
   601.8 1870.75   710.6 1914.13   735.3 1924.98   755.1 1932.14     770 1940.44
   794.7 1945.58   804.6 1951.24   809.5 1952.69   849.1 1959.03   898.6 1957.71
#Mann= 3 , 0 , 0
       0      .1       0   437.2    .045       0   452.2      .1       0
Bank Sta=437.2,452.2
XS Rating Curve= 0 ,0
Exp/Cntr=0.3,0.1

Type RM Length L Ch R = 1 ,296.9   ,86.1,84.1,80.6
XS GIS Cut Line= 4
     1837688.192      224730.364     1837446.977      225087.657
     1837396.582      225136.353     1837194.436      225493.081
#Sta/Elev= 30
       0 1986.14    44.6 1983.32   104.1 1965.84   148.6 1958.57   227.9 1942.21
   272.5 1922.11     327 1902.74   376.6 1870.23   401.4 1849.51   416.2 1838.55
   426.1 1833.14   439.3 1828.18   454.3  1824.2   454.5 1824.18   477.8  1827.3
   506.1  1841.5   525.9 1848.13   540.7 1849.01   560.4 1847.38   570.3 1848.42
   619.7 1869.08   644.4 1877.48   669.1 1883.52   708.6 1900.21   753.1 1909.96
   827.2 1930.47     847 1928.02   861.8 1929.12   876.6 1933.87   911.2 1941.57
#Mann= 3 , 0 , 0
       0      .1       0   439.3    .045       0   454.3      .1       0
Bank Sta=439.3,454.3
XS Rating Curve= 0 ,0
Exp/Cntr=0.3,0.1

Type RM Length L Ch R = 1 ,212.8   ,72.9,73.9,74.6
XS GIS Cut Line= 3
     1837643.734      224711.087     1837353.546      225068.013
     1837137.019       225468.16
#Sta/Elev= 30
       0 1959.54    29.7 1951.87    79.1 1930.29    98.9 1924.49   113.8 1924.16
   192.9 1929.87   227.5 1923.23   326.5  1880.2   395.7 1839.86   405.6 1835.62
   421.5 1831.03   430.3 1829.81   436.5 1831.27     465 1839.44     485 1847.31
     535 1844.13     575 1839.24     580 1839.91     660 1863.47     725 1875.76
     780 1893.28     840 1903.25     860 1902.87     865 1905.64     870 1910.22
     875 1911.18     880 1914.08     895  1926.2     905 1932.73     915 1936.18
#Mann= 3 , 0 , 0
       0      .1       0   421.5    .045       0   436.5      .1       0
Bank Sta=421.5,436.5
XS Rating Curve= 0 ,0
Exp/Cntr=0.3,0.1

Type RM Length L Ch R = 1 ,138.9   ,62.6,60.5,58.4
XS GIS Cut Line= 4
     1837643.809      224676.562     1837355.986      224954.508
     1837216.308      225119.583     1837094.971      225461.019
#Sta/Elev= 30
       0 1956.41    34.6 1945.35      84 1924.72   123.5 1911.99   143.2 1909.51
   182.8 1910.27   212.4  1909.6   227.2 1908.29     247 1905.03   335.9 1867.37
   370.5 1849.51   434.5 1828.25     442 1826.55   444.4 1826.24     457 1826.49
   542.6 1832.74   616.4 1831.72   685.8  1841.1   740.4  1840.8   745.4 1841.79
   775.2 1852.83     810 1863.92   844.7 1872.05   899.3 1883.18   904.3 1885.11
   924.1 1895.97     934  1897.8     944 1901.16   953.9 1907.94   978.7 1909.08
#Mann= 3 , 0 , 0
       0      .1       0     442    .045       0     457      .1       0
Bank Sta=442,457
XS Rating Curve= 0 ,0
Exp/Cntr=0.3,0.1

Type RM Length L Ch R = 1 ,78.4    ,76.5,70.4,64.3
XS GIS Cut Line= 4
     1837643.942      224661.562     1837295.784      224927.128
     1837189.049      225079.606     1837077.232      225469.696
#Sta/Elev= 30
       0 1955.35    29.9  1945.1    79.6 1924.95   149.3 1901.26   159.2  1899.5
     214 1895.95   233.9 1893.71   243.8 1891.65   318.5 1860.01   373.2 1834.12
   388.1 1828.21     408 1825.88   437.9    1820   467.6 1818.87   482.6 1818.61
   511.4 1817.92   540.7 1820.15     575 1820.55   599.5 1819.76     629 1817.21
   757.6 1836.47   782.4 1838.92   807.1 1847.23   831.8 1854.06   930.8 1876.74
   945.7 1881.88   960.5 1890.43   980.3 1893.51    1010 1903.04  1029.8 1906.33
#Mann= 3 , 0 , 0
       0      .1       0   467.6    .045       0   482.6      .1       0
#XS Ineff= 2 , 0
                          570.07         1820.58
Permanent Ineff=
       F       F
Bank Sta=467.6,482.6
XS Rating Curve= 0 ,0
Exp/Cntr=0.3,0.1

Type RM Length L Ch R = 1 ,8       ,0.2,8,15.7
XS GIS Cut Line= 4
     1837640.987      224638.468     1837239.875      224857.242
     1837154.742      225089.772     1837056.877      225480.771
#Sta/Elev= 30
       0 1949.47    79.5 1925.62   114.2 1909.83   158.9 1893.55   218.5 1878.53
   258.2 1866.03   322.8 1838.62   362.5 1825.14   456.9 1809.47   510.2 1803.54
   525.2 1803.23   531.2 1803.09     546 1804.55   570.8 1810.78   590.6 1813.16
   615.4 1812.91     660 1815.62   709.5  1814.5   744.3 1817.17   764.2 1821.65
   794.1 1830.78   848.8 1842.37   863.8 1843.92   913.5 1853.27   978.2 1867.35
  1003.1 1874.24    1023 1883.44  1077.7    1896  1092.6 1898.03  1107.6 1898.14
#Mann= 3 , 0 , 0
       0      .1       0   510.2    .045       0   525.2      .1       0
Bank Sta=510.2,525.2
XS Rating Curve= 0 ,0
Exp/Cntr=0.3,0.1

Chan Stop Cuts=-1
Use User Specified Reach Order=0